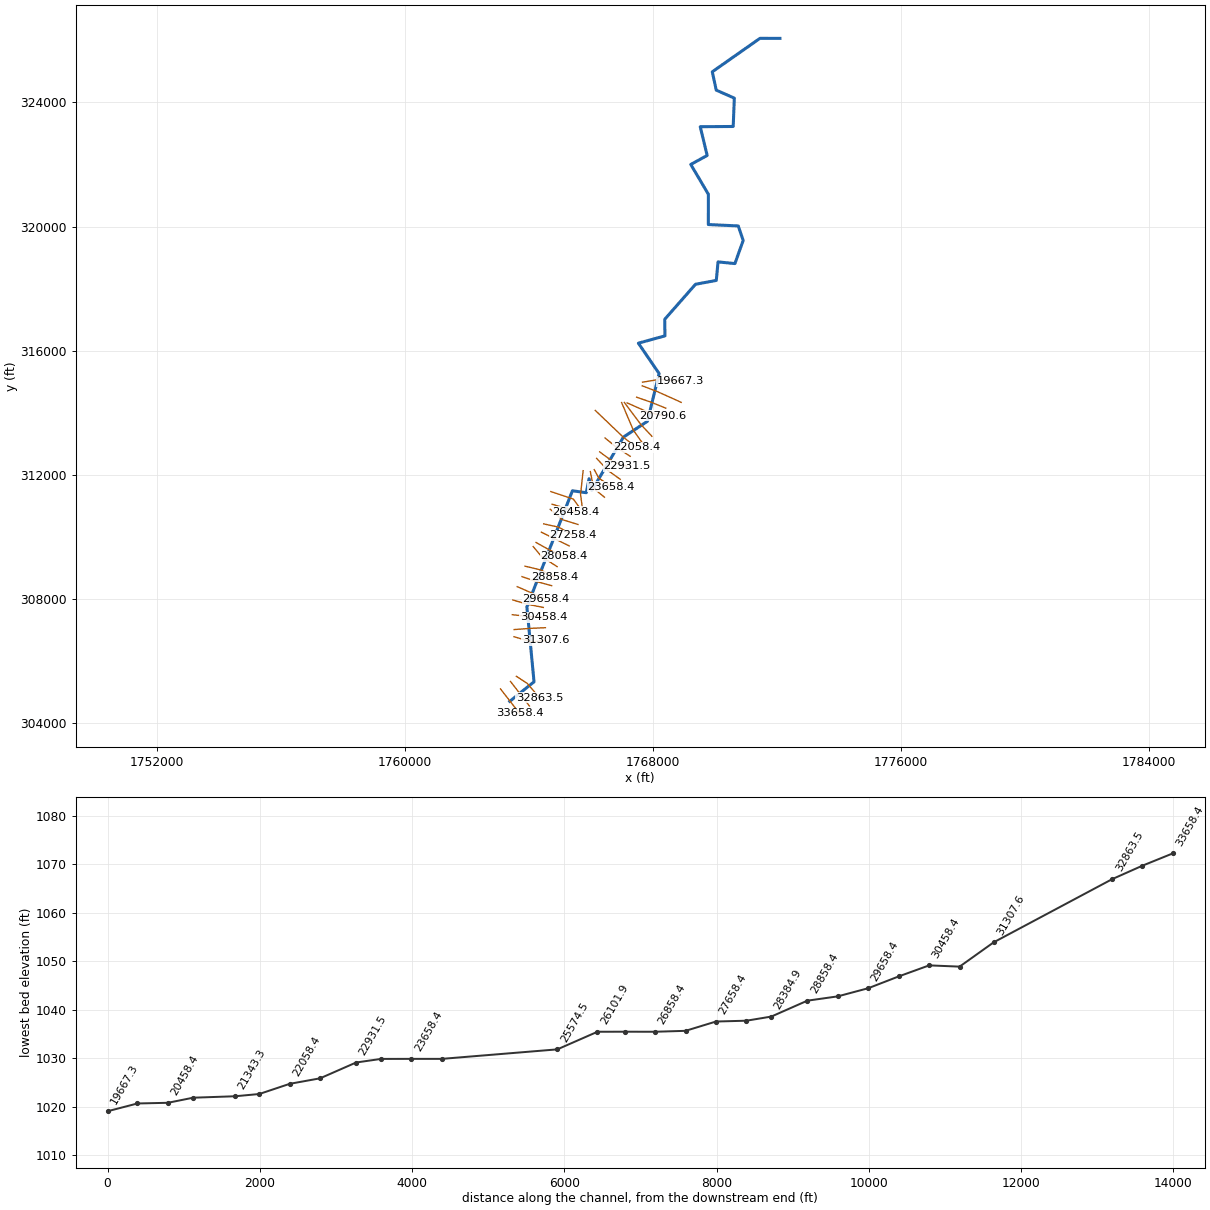
--- ThmasFk.prj (project) ---

Proj Title=ThmasFk
Current Plan=p01
Default Exp/Contr=0,0
English Units
Geom File=g01
Flow File=f01
Plan File=p01
BEGIN DESCRIPTION:
END DESCRIPTION:
DSS Export Rating Curves= 0
DSS Export Rating Curve Sorted= 0
DSS Export Volume Flow Curves= 0
DXF OffsetX= 0
DXF OffsetY= 0
DXF ScaleX= 0
DXF ScaleY= 0

--- ThmasFk.p01 (plan) ---

Plan Title=Floodplain
Program Version=4.00
Geom File=g01
Flow File=f01
K Sum by GR=0
Std Step Tol=0.01
Critical Tol=0.01
Num of Std Step Trials=20
Max Error Tol=0.3
Flow Tol Ratio=0.001
Split Flow NTrial=30
Split Flow Tol=0.02
Split Flow Ratio=0.02
Log Output Level=0
Friction Slope Method=1
Unsteady Friction Slope Method=2
Unsteady Bridges Friction Slope Method=1
Global Log Level=0
CheckData=False
Run HTab=0
Run UNet=0
Run PostProcess=0
UNET Theta=0
UNET Theta Warmup=0
UNET ZTol=0
UNET ZSATol=0
UNET MxIter=0
UNET MaxInSteps=0
UNET DtIC=0
UNET DtMin=0
UNET MaxCRTS=0
UNET WFStab=0
UNET SFStab=0
UNET WFX=0
UNET SFX=0
UNET DSS MLevel=0
UNET DZMax Abort=0
UNET Convert EG Bridges=0
UNET Use Existing IB Tables=0
UNET Froude Limit=0
UNET Froude Power=0
Write IC File=0
Echo Input=False
Echo Output=False
Write Detailed=0

--- ThmasFk.f01 (steady flow) ---

Flow Title=NFF Regression Equation
Program Version=4.00
Number of Profiles= 1
Profile Names=P100yr
River Rch & RM=ThmasFk,Main            ,33658.4
574.1792
River Rch & RM=ThmasFk,Main            ,31307.6
613.3953
River Rch & RM=ThmasFk,Main            ,31307.6
 918.619
River Rch & RM=ThmasFk,Main            ,30458.4
982.5868
River Rch & RM=ThmasFk,Main            ,28858.4
1086.566
River Rch & RM=ThmasFk,Main            ,28384.9
1137.642
River Rch & RM=ThmasFk,Main            ,26101.9
1226.441
River Rch & RM=ThmasFk,Main            ,24058.4
1585.619
River Rch & RM=ThmasFk,Main            ,23658.4
1605.573
River Rch & RM=ThmasFk,Main            ,19255.4
1757.195
River Rch & RM=ThmasFk,Main            ,14170.3
1950.802
River Rch & RM=ThmasFk,Main            ,13736.2
2572.222
River Rch & RM=ThmasFk,Main            ,10812.7
3486.991
River Rch & RM=ThmasFk,Main            ,58.4
3856.713
Boundary for River Rch & Prof#=ThmasFk,Main            , 1
Up Type= 0
Dn Type= 3
Dn Slope=0.003407
DSS Import GetInterval= 0
DSS Import GetPeak= 0
DSS Import FillOption= 0

--- ThmasFk.g01 (geometry) ---

Geom Title=USGS 3m DEM
Program Version=4.00

River Reach=ThmasFk         ,Main
Reach XY= 30
     1763377.428      304697.612     1764160.105      305326.912
     1763929.395         307740.     1765397.939      311482.656
     1765845.364       311421.31     1765935.834      311870.565
     1766027.008      311495.838     1767043.662      313211.722
     1767818.543      313724.063     1768194.887      315260.825
     1767525.741      316239.929     1768383.549      316475.528
      1768375.05      317008.496     1769368.025       318137.88
     1770038.835      318262.986     1770095.999      318859.126
     1770640.079      318806.045     1770906.504       319551.22
     1770747.262       320018.74     1769782.617      320063.655
     1769783.638      321040.549     1769216.081      322000.089
     1769744.849      322289.992     1769521.296      323216.867
     1770584.956      323224.013     1770620.684      324138.638
     1770037.814      324394.855     1769910.216      324986.912
     1771448.542      326064.863     1772091.638      326063.843

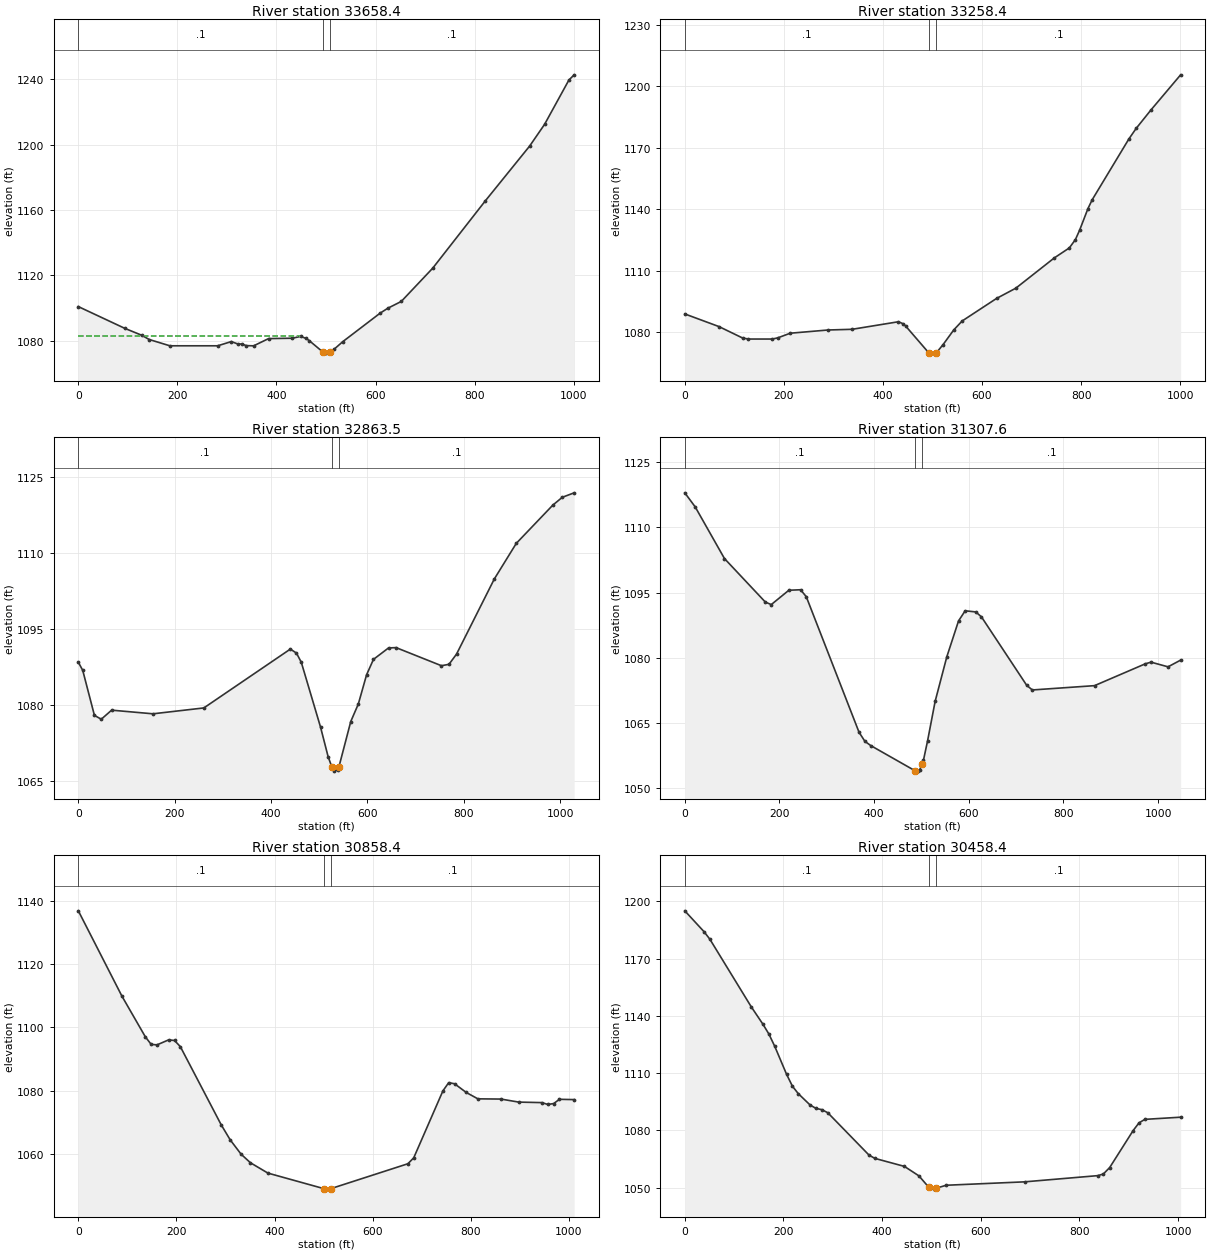
Type RM Length L Ch R = 1 ,33658.4 ,400.129,400,399.871
XS GIS Cut Line= 3
      1763077.41      305098.348     1763385.311      304703.764
     1763693.213      304309.179
#Sta/Elev= 30
       0 1100.77    93.7 1087.46   128.1  1083.2   143.1 1080.61   184.8 1076.76
   281.3 1076.76   308.8 1079.34   322.1 1077.87   330.6 1077.84   338.9 1076.87
   353.9 1076.74   384.1 1081.17   432.1  1081.4     449 1082.51   459.4 1081.32
   465.9    1080     493 1073.13   499.8 1072.27     508  1073.1   516.7 1074.75
   533.6 1079.23   609.4 1096.78     625  1099.8     652 1103.93   715.4 1124.28
   821.7 1165.55   911.2 1199.12   941.3  1212.4   990.4 1239.54    1001 1242.72
#Mann= 3 , 0 , 0
       0      .1       0     493    .045       0     508      .1       0
#XS Ineff= 2 , 0
          447.85 1082.64
Permanent Ineff=
       F       F
Bank Sta=493,508
XS Rating Curve= 0 ,0
Exp/Cntr=0.3,0.1

Type RM Length L Ch R = 1 ,33258.4 ,393.674,394.903,396.132
XS GIS Cut Line= 3
     1763400.411      305339.043     1763706.047      304942.701
     1764011.683      304546.359
#Sta/Elev= 30
       0 1088.86      69 1082.69   116.6 1077.12   128.2 1076.61   176.6 1076.61
   187.5 1077.17   212.9 1079.45   289.1 1081.02   337.8 1081.36   431.4 1085.05
   441.4    1084   446.4 1082.81     493 1069.75   493.3 1069.73     508 1069.93
   521.4 1073.88     543 1081.06     560 1085.43   629.4 1096.43   668.3 1101.43
     746 1116.21   776.3 1121.08   788.5 1125.11     797 1129.68   813.9 1140.28
   822.4 1144.56   896.2 1174.14   911.2 1179.41   941.2 1188.45    1001 1205.57
#Mann= 3 , 0 , 0
       0      .1       0     493    .045       0     508      .1       0
Bank Sta=493,508
XS Rating Curve= 0 ,0
Exp/Cntr=0.3,0.1

Type RM Length L Ch R = 1 ,32863.5 ,1542.716,1555.902,1569.089
XS GIS Cut Line= 3
     1763590.613      305504.471     1763939.841      305275.667
     1764339.149       304812.52
#Sta/Elev= 30
       0 1088.47     9.1 1086.88    33.4 1077.98    47.6 1077.22    69.1 1079.01
   154.9 1078.29   260.5 1079.45     440 1091.07   452.7 1090.28   462.7 1088.47
   502.7 1075.65   518.4 1069.82     526 1067.82   530.1 1066.97   538.5 1067.19
     541 1067.88   565.4 1076.77   581.1 1080.23   598.2 1085.99   612.5 1089.04
   643.8  1091.3   659.5 1091.36   753.5 1087.79   769.2 1088.06   784.9 1090.08
   863.3 1104.92   908.9 1111.95   984.7  1119.5  1004.4 1121.05    1029 1121.93
#Mann= 3 , 0 , 0
       0      .1       0     526    .045       0     541      .1       0
Bank Sta=526,541
XS Rating Curve= 0 ,0
Exp/Cntr=0.3,0.1

Type RM Length L Ch R = 1 ,31307.6 ,441.103,449.194,456.591
XS GIS Cut Line= 3
     1763514.345      306778.951     1764089.117      306611.918
     1764535.451      306660.433
#Sta/Elev= 30
       0 1117.93      22 1114.69    83.8 1102.82   170.3  1092.8   182.7 1092.24
   219.8 1095.53   244.5 1095.65   256.6 1094.06   368.1 1062.89   380.5  1060.8
   392.9 1059.82   486.4 1054.04   491.8 1053.95   496.5  1054.3   501.4 1055.65
   504.1  1056.4   512.9 1060.91   528.9    1070   553.6 1080.25   578.3 1088.48
   592.3 1090.81   614.8 1090.55   626.8  1089.4   722.3 1073.68   734.2 1072.61
   865.6  1073.6   973.1 1078.63     985    1079  1020.9 1077.93  1047.5 1079.47
#Mann= 3 , 0 , 0
       0      .1       0   486.4    .045       0   501.4      .1       0
Bank Sta=486.4,501.4
XS Rating Curve= 0 ,0
Exp/Cntr=0.3,0.1

Type RM Length L Ch R = 1 ,30858.4 ,404.116,400,398.088
XS GIS Cut Line= 3
     1763517.965      307009.942     1764024.083      307047.943
      1764527.09      307070.387
#Sta/Elev= 30
       0 1136.83      89 1109.85   136.6 1097.04   148.5 1094.64   160.4 1094.49
   184.2 1096.07   196.1 1095.87     208 1093.93   291.4 1069.21   309.6  1064.5
   331.8 1059.97   350.9 1057.25   386.6 1053.98     500  1049.1   505.7 1048.92
     515 1049.08     672 1056.94   683.9 1058.81   743.4 1079.96   755.2 1082.55
   767.1 1082.21   790.9 1079.46   814.7 1077.44   861.7 1077.37   897.9 1076.41
   945.4 1076.25   957.3 1075.66   969.2 1075.95     981 1077.29    1011  1077.2
#Mann= 3 , 0 , 0
       0      .1       0     500    .045       0     515      .1       0
Bank Sta=500,515
XS Rating Curve= 0 ,0
Exp/Cntr=0.3,0.1

Type RM Length L Ch R = 1 ,30458.4 ,404.289,400,396.277
XS GIS Cut Line= 3
     1763461.061      307489.561     1763959.957      307433.771
     1764462.688      307411.302
#Sta/Elev= 30
       0 1195.07      39 1184.13    50.9 1180.16   134.6  1144.8   158.5 1135.59
   170.4 1130.52   182.4 1124.02   206.2 1109.45   218.2 1103.13   230.1 1099.22
     254 1093.29     266 1091.49   277.9 1090.84   289.9 1089.22   373.5 1067.01
   385.4 1065.29   445.2  1061.1   474.6 1056.14   494.5  1050.2   504.9 1049.18
   509.5 1049.65   529.9 1051.21     689    1053   837.1 1056.25   848.4 1057.09
   861.4  1060.5     909 1079.91   920.9 1083.94   932.7 1085.75  1005.2 1086.89
#Mann= 3 , 0 , 0
       0      .1       0   494.5    .045       0   509.5      .1       0
Bank Sta=494.5,509.5
XS Rating Curve= 0 ,0
Exp/Cntr=0.3,0.1

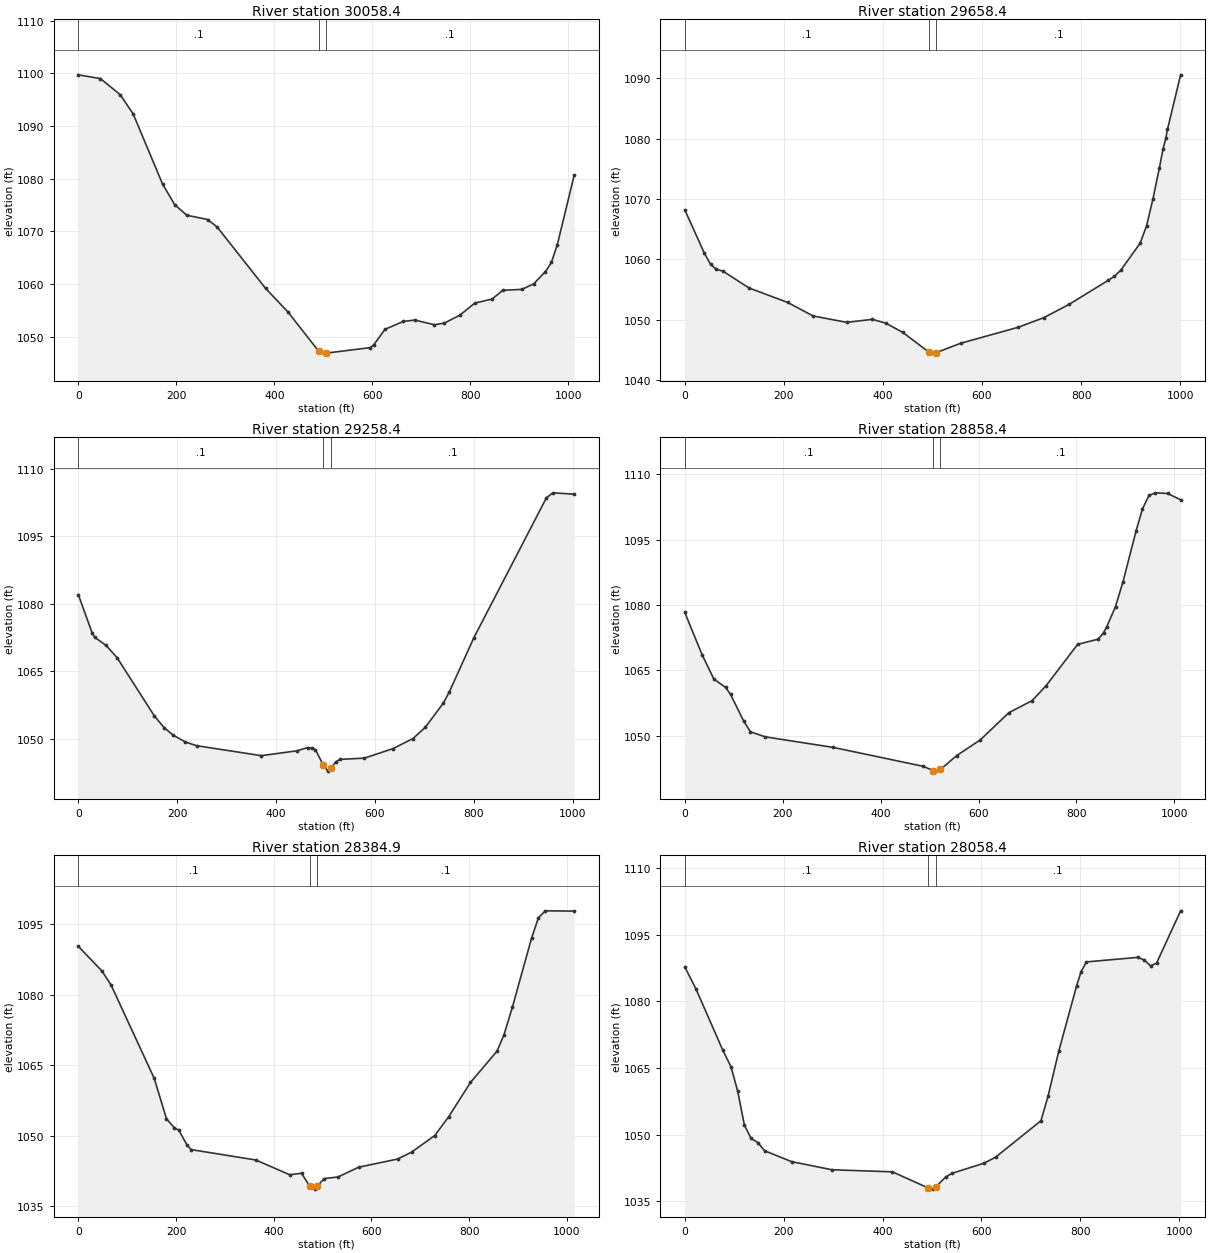
Type RM Length L Ch R = 1 ,30058.4 ,403.422,400,394.503
XS GIS Cut Line= 3
     1763477.355       307963.39     1763955.498      307823.175
     1764459.441      307723.628
#Sta/Elev= 30
       0 1099.72    45.1    1099    85.3 1095.97     112 1092.29   171.9 1078.99
   196.6 1075.09   221.4 1073.07   263.9 1072.26   283.2 1070.85   382.2 1059.19
   427.7 1054.73   490.8 1047.24   505.8  1046.9   595.6 1047.94   602.6 1048.43
   625.9 1051.42   663.1 1052.91   686.5 1053.18   726.9 1052.28   747.2 1052.61
     779 1054.12   809.1 1056.39   844.6 1057.17   866.3 1058.83   905.1    1059
   929.1 1060.03   953.5 1062.39   965.6 1064.12   977.7 1067.51    1012 1080.65
#Mann= 3 , 0 , 0
       0      .1       0   490.8    .045       0   505.8      .1       0
Bank Sta=490.8,505.8
XS Rating Curve= 0 ,0
Exp/Cntr=0.3,0.1

Type RM Length L Ch R = 1 ,29658.4 ,398.127,400,403.312
XS GIS Cut Line= 3
     1763618.373      308392.527     1764077.442      308193.136
      1764536.51      307993.746
#Sta/Elev= 30
       0 1068.21      39 1061.13      52 1059.18      63 1058.41    77.8 1058.02
   129.6 1055.27   207.4 1052.88   259.1 1050.63   326.7 1049.57   378.8 1050.07
   405.9 1049.43   440.3  1047.9     493 1044.62     505 1044.47     508 1044.57
   556.8  1046.1   673.3 1048.76   725.1 1050.36   775.9 1052.55   854.5 1056.52
   867.4 1057.21   880.4 1058.23   919.2 1062.68   932.2 1065.55   945.1 1070.03
   958.1 1075.15   965.4 1078.29     971 1080.06   974.4 1081.55    1001  1090.6
#Mann= 3 , 0 , 0
       0      .1       0     493    .045       0     508      .1       0
Bank Sta=493,508
XS Rating Curve= 0 ,0
Exp/Cntr=0.3,0.1

Type RM Length L Ch R = 1 ,29258.4 ,397.861,400,395.55
XS GIS Cut Line= 3
     1763769.824         308717.     1764245.983      308555.358
     1764728.824      308425.164
#Sta/Elev= 30
       0 1082.02    28.3 1073.39    33.2 1072.53    56.3 1070.72    78.5 1067.99
   153.7 1055.07   173.6 1052.45   191.3 1050.82   216.4 1049.27   239.2 1048.44
   370.2 1046.23   442.1  1047.3   463.8 1048.02   473.2 1047.88   479.7 1047.54
   495.3 1044.16   504.7 1042.79   510.3 1043.38   520.6 1044.83   529.3  1045.4
   578.7 1045.68   636.8 1047.81   676.9 1050.03   701.5 1052.49   738.4 1057.92
   750.7 1060.47   799.8 1072.39   946.7 1103.51   959.7 1104.64  1002.9 1104.34
#Mann= 3 , 0 , 0
       0      .1       0   495.3    .045       0   510.3      .1       0
Bank Sta=495.3,510.3
XS Rating Curve= 0 ,0
Exp/Cntr=0.3,0.1

Type RM Length L Ch R = 1 ,28858.4 ,481.788,473.554,470.102
XS GIS Cut Line= 3
     1763869.676      309053.535     1764370.126      308933.274
     1764816.172       308711.82
#Sta/Elev= 30
       0  1078.3    35.5 1068.57    59.2 1063.06    83.2 1061.11    93.4 1059.52
   120.2  1053.4     134 1050.93   164.1 1049.77   303.4 1047.34   487.2    1043
   507.2 1042.03     511  1041.9   522.2 1042.28     555 1045.45   603.5 1049.06
   661.8  1055.3   709.5 1058.09   737.9  1061.5   802.3 1070.98   844.2 1072.18
   855.3 1073.67     862 1075.08   879.7 1079.67   895.1 1085.39   921.6 1096.96
   934.8 1102.08   948.1 1105.17   961.3 1105.76     986 1105.61  1012.7 1104.17
#Mann= 3 , 0 , 0
       0      .1       0   507.2    .045       0   522.2      .1       0
Bank Sta=507.2,522.2
XS Rating Curve= 0 ,0
Exp/Cntr=0.3,0.1

Type RM Length L Ch R = 1 ,28384.9 ,325.292,326.446,329.817
XS GIS Cut Line= 3
     1764133.454      309684.479     1764401.121       309364.32
     1764902.827      309039.317
#Sta/Elev= 30
       0 1090.29    48.7 1084.99    67.2 1082.02   155.2 1062.23   180.5 1053.59
   196.8 1051.64   205.7 1051.18   222.6 1047.97     231 1047.03   363.4 1044.82
   432.7 1041.68   456.9    1042     474  1039.2   485.1 1038.62     489 1039.25
   503.4 1040.86   531.7 1041.21   574.1 1043.29   653.5 1045.02   682.6 1046.51
   729.7 1050.03     758 1053.99   802.8 1061.32     857 1067.96   871.2 1071.39
   888.6 1077.33   927.8 1091.99   941.9 1096.37   956.1 1097.84  1015.1 1097.78
#Mann= 3 , 0 , 0
       0      .1       0     474    .045       0     489      .1       0
Bank Sta=474,489
XS Rating Curve= 0 ,0
Exp/Cntr=0.3,0.1

Type RM Length L Ch R = 1 ,28058.4 ,398.797,400,398.986
XS GIS Cut Line= 3
     1764225.654      309816.751     1764661.916      309572.379
     1765122.825      309370.735
#Sta/Elev= 30
       0 1087.75    22.4 1082.85    76.6 1069.09    93.4 1065.32     107  1059.8
   120.6 1052.17   134.2 1049.17   147.8 1048.24   161.5  1046.4   215.9 1043.96
   297.5 1042.13     420 1041.66   492.5 1038.03   501.6 1037.77   507.5 1038.23
   527.5 1040.47   540.5 1041.32   605.3  1043.6   628.6 1044.94   720.5 1053.15
   734.9 1058.67   756.6 1068.81   792.7 1083.51   801.7 1086.67   812.6 1088.88
   916.3  1089.9   929.2 1089.34   942.2 1087.98   954.4 1088.61  1003.1 1100.37
#Mann= 3 , 0 , 0
       0      .1       0   492.5    .045       0   507.5      .1       0
Bank Sta=492.5,507.5
XS Rating Curve= 0 ,0
Exp/Cntr=0.3,0.1

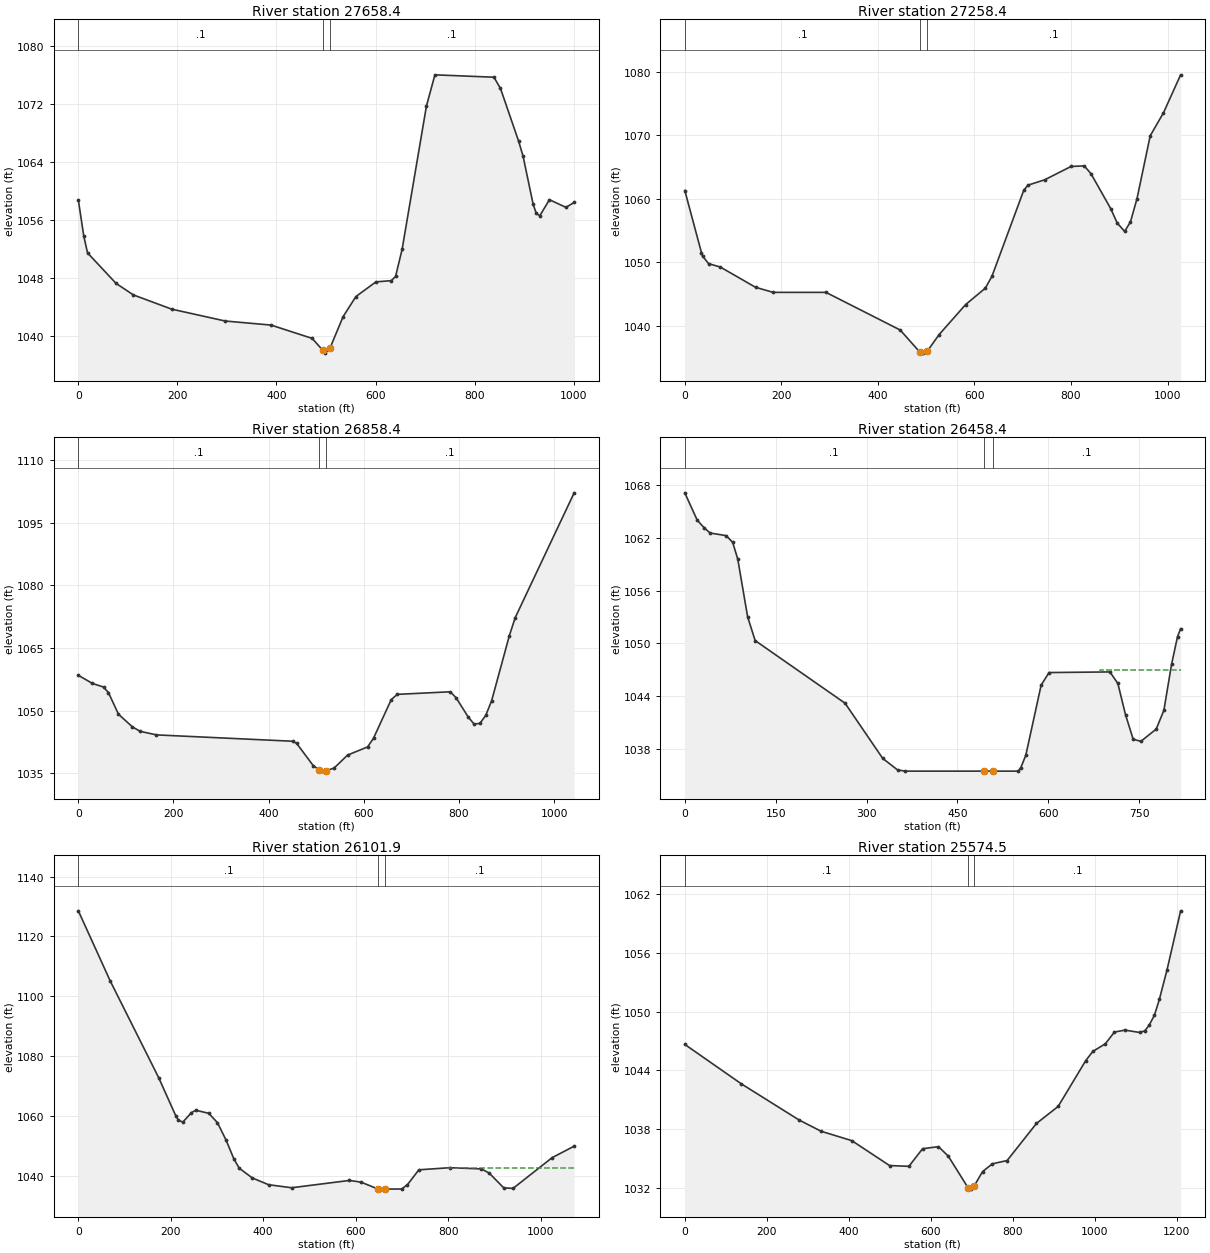
Type RM Length L Ch R = 1 ,27658.4 ,394.562,400,398.431
XS GIS Cut Line= 3
     1764397.306      310148.134     1764846.412      309927.219
     1765295.519      309706.305
#Sta/Elev= 30
       0 1058.73      11 1053.75    18.6 1051.43    76.2 1047.22   111.2 1045.63
   188.4 1043.67   296.5 1042.03   389.1 1041.47   472.2 1039.63     493 1038.03
   498.8  1037.6     508 1038.28   534.6 1042.64   560.4 1045.41   600.8 1047.43
   631.8  1047.6   640.5 1048.19   653.7 1051.93   702.8  1071.7   719.9    1076
     839 1075.67   852.2 1074.13     889 1066.82   897.9 1064.76   918.3 1058.11
   924.5  1056.9   931.6 1056.55   951.1 1058.77   984.5 1057.71    1001  1058.4
#Mann= 3 , 0 , 0
       0      .1       0     493    .045       0     508      .1       0
Bank Sta=493,508
XS Rating Curve= 0 ,0
Exp/Cntr=0.3,0.1

Type RM Length L Ch R = 1 ,27258.4 ,410.701,400,409.649
XS GIS Cut Line= 3
     1764472.703       310416.07     1764956.109      310310.003
     1765418.521      310046.541
#Sta/Elev= 30
       0 1061.29    34.5 1051.51    37.1 1050.94    49.3 1049.77    73.6 1049.24
   146.5 1046.05     183 1045.25   292.4 1045.25   446.2 1039.32   487.4  1035.8
     493 1035.68   502.4    1036   526.9 1038.61   581.5 1043.31   622.5 1045.91
   636.2 1047.77   702.1 1061.32   710.8 1062.13   745.5 1062.98   800.2 1065.08
   827.5 1065.17   841.4 1063.94   882.2 1058.45   895.8 1056.16   911.1 1054.85
   923.2 1056.35   936.8 1060.03   964.1 1069.91   991.5 1073.52  1027.1 1079.51
#Mann= 3 , 0 , 0
       0      .1       0   487.4    .045       0   502.4      .1       0
Bank Sta=487.4,502.4
XS Rating Curve= 0 ,0
Exp/Cntr=0.3,0.1

Type RM Length L Ch R = 1 ,26858.4 ,391.641,400,390.073
XS GIS Cut Line= 3
     1764682.507      310887.828     1765071.755      310552.584
     1765577.079      310397.638
#Sta/Elev= 30
       0 1058.45    29.6  1056.5      53 1055.63    63.3  1054.3    84.4 1049.12
   113.8 1046.08   129.8 1045.03   164.3 1044.17   450.6 1042.65     459 1042.13
   493.7 1036.82   506.2 1035.79   511.9 1035.49   521.2  1035.6   537.5 1036.21
     566 1039.33   608.1 1041.29   620.5 1043.37   657.8 1052.63   670.5 1053.88
   781.9  1054.5   794.1 1053.07   819.2 1048.53   831.6  1046.8     844  1046.9
   856.5 1048.85   868.9 1052.39   906.1 1067.96   918.5 1072.29  1042.3 1102.16
#Mann= 3 , 0 , 0
       0      .1       0   506.2    .045       0   521.2      .1       0
Bank Sta=506.2,521.2
XS Rating Curve= 0 ,0
Exp/Cntr=0.3,0.1

Type RM Length L Ch R = 1 ,26458.4 ,357.363,356.527,357.263
XS GIS Cut Line= 3
     1764741.893        311049.5     1765222.261      310908.977
     1765520.295      310798.718
#Sta/Elev= 30
       0 1067.09    20.4    1064    31.8 1063.13    41.8 1062.53    68.3 1062.23
      79 1061.47    87.4 1059.57   103.7 1053.01   116.1 1050.32   264.5 1043.21
   326.7 1036.94   351.1 1035.64   363.5  1035.5     493  1035.5     508  1035.5
   550.2  1035.5   554.5 1035.89   562.8  1037.3   588.1 1045.26   601.1 1046.69
   701.6 1046.76   714.7 1045.45   727.4 1041.89     740 1039.12   752.7 1038.88
     778 1040.27   790.7 1042.41   803.3 1047.61   813.2 1050.77   818.3 1051.67
#Mann= 3 , 0 , 0
       0      .1       0     493    .045       0     508      .1       0
#XS Ineff= 2 , 0
                          685.56         1046.95
Permanent Ineff=
       F       F
Bank Sta=493,508
XS Rating Curve= 0 ,0
Exp/Cntr=0.3,0.1

Type RM Length L Ch R = 1 ,26101.9 ,559.389,527.388,495.388
XS GIS Cut Line= 3
       1764700.4      311458.515     1765428.117      311215.943
     1765607.621      310968.519
#Sta/Elev= 30
       0 1128.57      69 1105.12   173.7 1072.81   211.2 1059.89   216.6  1058.6
     226 1057.88   244.8 1061.09   254.2 1061.88   282.3 1060.84   301.1 1057.69
   319.9  1051.8   336.4 1045.66     348 1042.51   376.2 1039.25   411.5 1036.97
   461.5 1035.95   586.7  1038.4   611.7 1037.82   649.1 1035.49   664.1  1035.5
   699.3 1035.53   711.8 1036.92   736.8 1041.95   804.1 1042.66   872.1 1042.25
   889.1 1040.84   920.4 1035.92   940.6 1035.74  1025.1 1046.01  1072.8 1049.86
#Mann= 3 , 0 , 0
       0      .1       0   649.1    .045       0   664.1      .1       0
#XS Ineff= 2 , 0
                          798.23         1042.69
Permanent Ineff=
       F       F
Bank Sta=649.1,664.1
XS Rating Curve= 0 ,0
Exp/Cntr=0.3,0.1

Type RM Length L Ch R = 1 ,25574.5 ,1487,1516.085,1533.872
XS GIS Cut Line= 3
     1765743.973      312130.583     1765660.987      311366.338
     1765719.204      310929.707
#Sta/Elev= 30
       0 1046.65   138.2 1042.61   278.5 1038.93   332.1 1037.78   407.5 1036.81
   499.3 1034.27   546.5 1034.19   579.9 1035.99   618.7  1036.2   642.6 1035.23
   690.8    1032   698.4 1031.86   705.8 1032.19   726.2 1033.65   750.1 1034.45
     786 1034.78   857.6 1038.57   910.5 1040.31   977.6 1044.98     995 1045.93
  1025.5 1046.71  1047.8 1047.91  1073.4 1048.11  1109.4 1047.87  1121.8 1048.04
  1132.4 1048.61  1145.3 1049.63  1157.3 1051.24    1176 1054.26  1209.2  1060.3
#Mann= 3 , 0 , 0
       0      .1       0   690.8    .045       0   705.8      .1       0
Bank Sta=690.8,705.8
XS Rating Curve= 0 ,0
Exp/Cntr=0.3,0.1

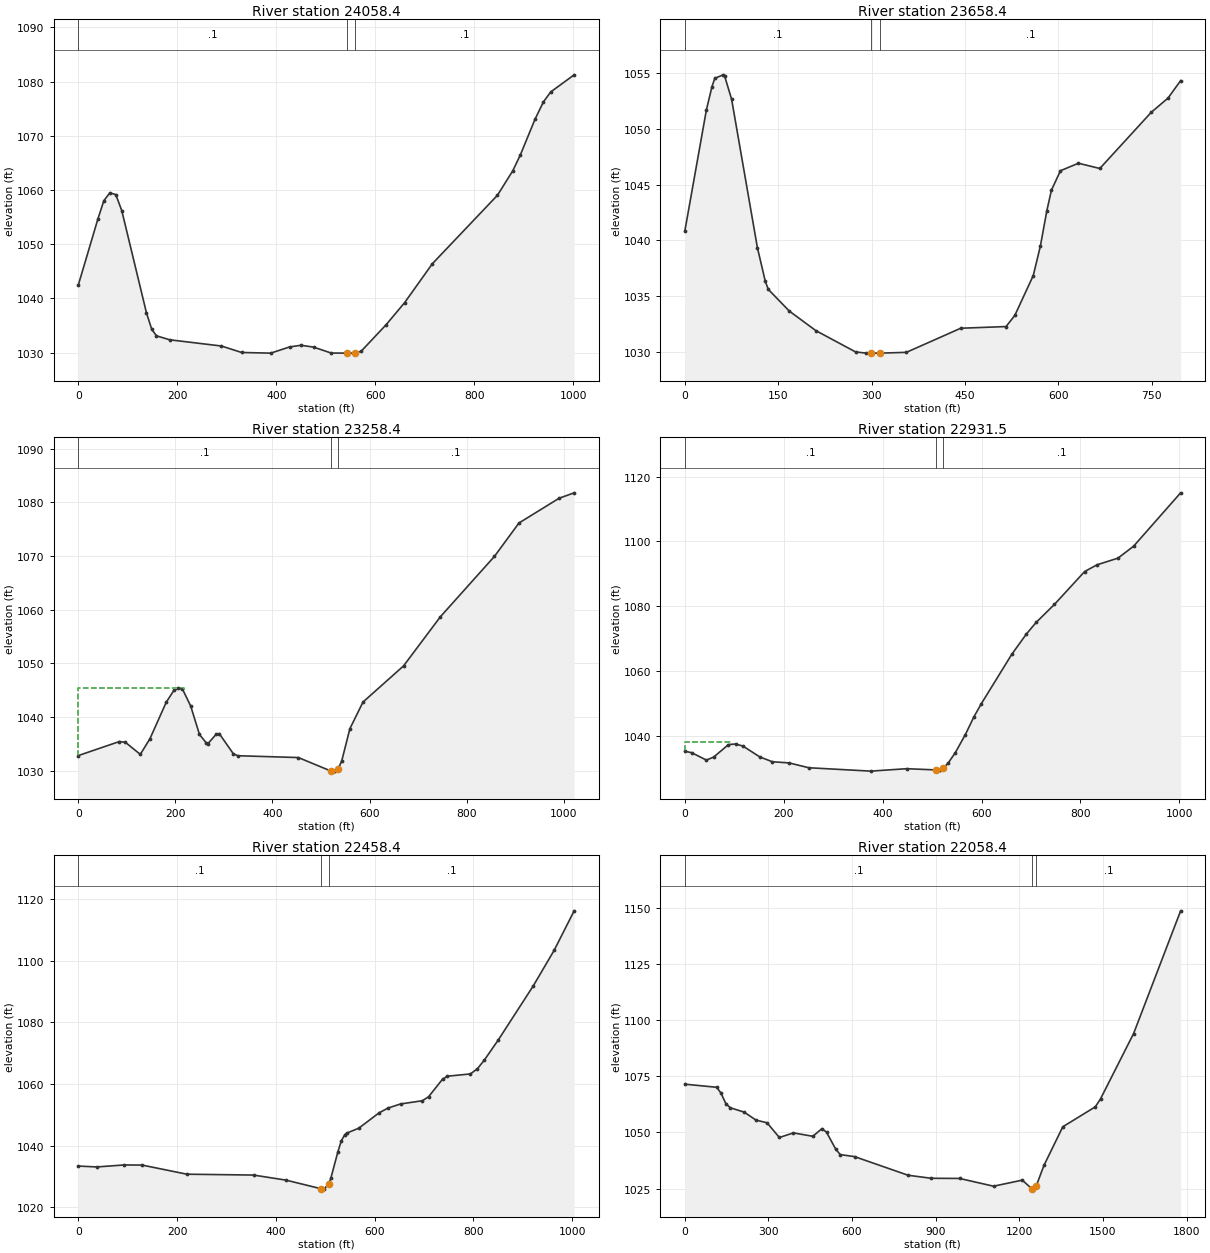
Type RM Length L Ch R = 1 ,24058.4 ,390.821,400,401.599
XS GIS Cut Line= 3
     1765976.741      312100.283     1766083.925      311560.325
     1766433.418      311274.988
#Sta/Elev= 30
       0 1042.48    39.4 1054.61    51.5 1058.01    63.6 1059.46    75.7 1059.15
    87.8 1056.18   137.7 1037.31   148.4 1034.27   157.9 1033.09   184.7 1032.36
   289.2 1031.21   329.9 1030.02   388.8  1029.9   426.8 1031.04   449.7 1031.35
   475.2 1031.01   510.7 1029.92     543  1029.9     558 1029.92   571.1 1030.22
   621.4  1035.1     659 1039.19   715.3  1046.4   846.7 1059.02   877.7 1063.54
     893 1066.47   922.8 1073.08   939.7 1076.26   954.3 1078.08  1001.7 1081.24
#Mann= 3 , 0 , 0
       0      .1       0     543    .045       0     558      .1       0
Bank Sta=543,558
XS Rating Curve= 0 ,0
Exp/Cntr=0.3,0.1

Type RM Length L Ch R = 1 ,23658.4 ,393.78,400,399.792
XS GIS Cut Line= 3
      1766102.75      312163.287     1766249.219      311894.526
     1766649.079      311610.626
#Sta/Elev= 30
       0 1040.82    34.7 1051.69    43.7 1053.78    48.2 1054.52    61.7 1054.83
    64.1  1054.7    75.2 1052.64   116.6 1039.35   129.3 1036.33   134.1 1035.61
   167.8 1033.67   210.4 1031.92   274.2 1030.01   291.3  1029.9   298.6  1029.9
   313.6  1029.9   355.9 1029.97   443.2 1032.13     516 1032.28   530.1 1033.28
   559.7 1036.85   571.1 1039.48   581.5 1042.65   588.9  1044.5   603.4 1046.24
   632.3 1046.91   666.6 1046.44     749 1051.46   776.2 1052.75   796.4 1054.31
#Mann= 3 , 0 , 0
       0      .1       0   298.6    .045       0   313.6      .1       0
Bank Sta=298.6,313.6
XS Rating Curve= 0 ,0
Exp/Cntr=0.3,0.1

Type RM Length L Ch R = 1 ,23258.4 ,322.807,326.964,326.552
XS GIS Cut Line= 3
     1766179.056      312527.275     1766539.231      312141.015
     1766940.322      311853.597
#Sta/Elev= 30
       0 1032.79    84.8 1035.41    97.1 1035.25   127.7 1033.01   147.5 1035.92
   181.1 1042.72   197.3    1045   206.3 1045.31   214.6 1045.18   231.5 1042.02
   249.6 1036.72   263.3 1035.18     267 1035.01   284.4  1036.8   290.3 1036.89
   319.2 1033.15   328.3 1032.76   453.4 1032.42   520.6  1029.9   528.1 1029.89
   535.6 1030.37   542.7 1031.79   559.5  1037.8   586.5 1042.76   670.1  1049.5
     746 1058.66   857.3  1069.9   907.9 1076.13   990.6 1080.74  1021.6 1081.75
#Mann= 3 , 0 , 0
       0      .1       0   520.6    .045       0   535.6      .1       0
#XS Ineff= 2 , 0
          216.83 1045.41
Permanent Ineff=
       F       F
Bank Sta=520.6,535.6
XS Rating Curve= 0 ,0
Exp/Cntr=0.3,0.1

Type RM Length L Ch R = 1 ,22931.5 ,474.029,473.036,474.548
XS GIS Cut Line= 3
     1766278.582      312737.385     1766733.662      312398.705
     1767153.136      312282.296
#Sta/Elev= 30
       0 1035.29    14.1 1034.83    43.7 1032.55    58.5  1033.5    88.1 1037.31
   102.9 1037.53   117.7 1036.86   151.6 1033.54   176.9 1032.05     211 1031.68
   250.9 1030.19   376.2 1029.15   448.6  1029.9   507.7 1029.52   516.5 1029.52
   522.7 1030.12   532.1 1031.54   546.9 1034.82   567.3 1040.42   584.7 1045.92
   599.6 1049.95   661.2 1065.19   690.6 1071.41   710.5 1075.03   747.4 1080.57
   808.5 1090.71   833.7  1092.8     876 1094.85   907.6 1098.54  1002.6 1114.99
#Mann= 3 , 0 , 0
       0      .1       0   507.7    .045       0   522.7      .1       0
#XS Ineff= 2 , 0
           93.53 1038.15
Permanent Ineff=
       F       F
Bank Sta=507.7,522.7
XS Rating Curve= 0 ,0
Exp/Cntr=0.3,0.1

Type RM Length L Ch R = 1 ,22458.4 ,401.959,400,398.072
XS GIS Cut Line= 3
     1766450.809      313184.729     1766838.184      312868.853
     1767261.857      312595.398
#Sta/Elev= 30
       0 1033.37    37.5 1033.08    93.2 1033.73   129.4 1033.68   219.8 1030.73
   354.8 1030.45   420.5 1028.81   492.3 1025.99   497.1 1025.89   507.3 1027.56
   511.4 1029.45   525.5 1037.91   532.6 1041.56   539.7 1043.56   543.4 1044.03
   567.9 1045.64   609.1 1050.63     627 1052.16   652.7 1053.51   696.7 1054.54
   709.2 1055.83   737.5 1061.51   747.2 1062.49     794 1063.24   808.1  1064.9
   822.3 1067.75   850.5 1074.26   921.2 1091.76   963.6 1103.31  1004.1 1116.11
#Mann= 3 , 0 , 0
       0      .1       0   492.3    .045       0   507.3      .1       0
Bank Sta=492.3,507.3
XS Rating Curve= 0 ,0
Exp/Cntr=0.3,0.1

Type RM Length L Ch R = 1 ,22058.4 ,408.925,400,393.452
XS GIS Cut Line= 3
     1766135.861      314073.268     1767042.055      313207.831
     1767458.206      312886.455
#Sta/Elev= 30
       0 1071.51   114.5 1070.12   129.4 1067.61   147.3 1062.84     163    1061
     213 1059.06   255.4  1055.5   295.1 1054.31   339.3 1047.75   389.7  1049.8
   459.2 1048.29   492.1  1051.7   508.5 1050.09   541.3  1042.6   557.6 1040.14
   609.2 1039.23   801.2 1030.93   884.2 1029.58   985.9 1029.51  1107.7 1026.05
  1210.8 1028.76  1245.6 1024.85  1247.3 1024.75  1260.6 1026.08  1288.5  1035.3
  1356.2 1052.53  1472.8 1061.41  1491.7 1065.01  1610.2 1094.06  1778.9 1148.73
#Mann= 3 , 0 , 0
       0      .1       0  1245.6    .045       0  1260.6      .1       0
Bank Sta=1245.6,1260.6
XS Rating Curve= 0 ,0
Exp/Cntr=0.3,0.1

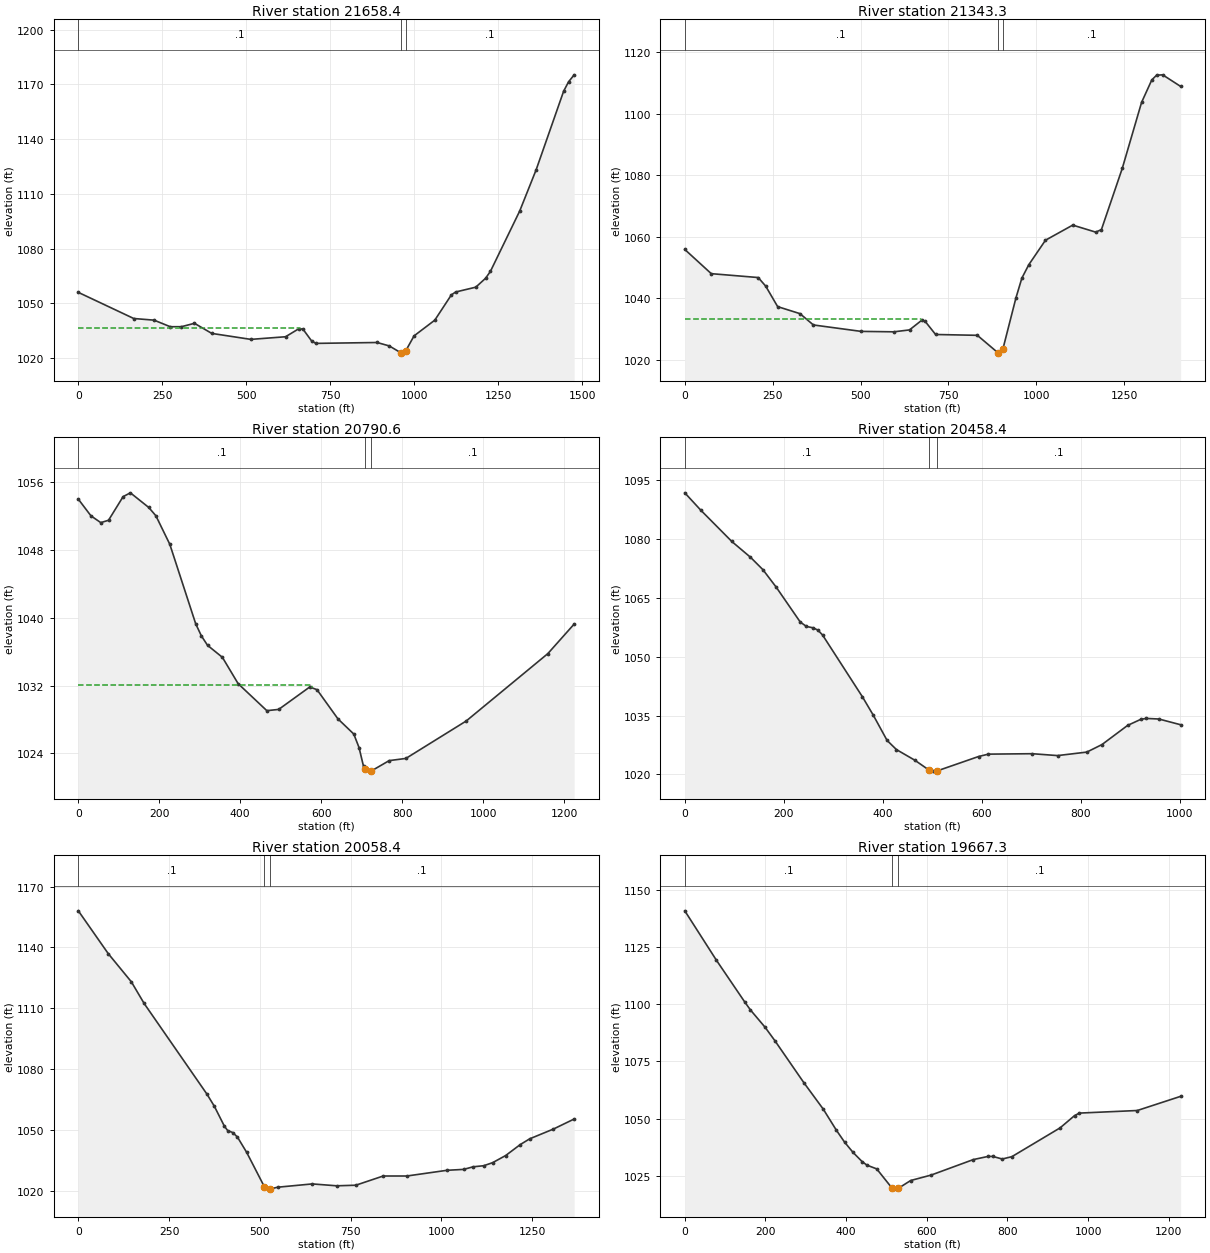
Type RM Length L Ch R = 1 ,21658.4 ,308.935,315.148,318.416
XS GIS Cut Line= 3
     1766985.174      314326.652     1767363.712      313437.117
     1767656.554      313021.432
#Sta/Elev= 30
       0 1055.97   164.9 1041.64   225.5 1040.73   273.5 1037.13   306.8 1037.14
   345.5 1039.01   397.1 1033.46   513.2 1030.19   616.5 1031.63   655.2 1035.94
   668.1 1035.87   693.9 1029.37   706.8 1027.99     889 1028.48   925.2 1026.59
   959.2 1022.89   961.4 1022.65   974.2 1023.93   998.8  1032.1  1060.6 1040.74
  1109.8 1054.58  1122.5 1056.17  1182.5 1058.82  1211.5 1063.68    1226 1067.47
  1313.2  1100.6  1362.2 1123.25  1443.9 1166.31  1458.4 1171.41  1475.2 1175.29
#Mann= 3 , 0 , 0
       0      .1       0   959.2    .045       0   974.2      .1       0
#XS Ineff= 2 , 0
          658.99 1036.65
Permanent Ineff=
       F       F
Bank Sta=959.2,974.2
XS Rating Curve= 0 ,0
Exp/Cntr=0.3,0.1

Type RM Length L Ch R = 1 ,21343.3 ,538.828,552.633,566.884
XS GIS Cut Line= 3
      1767072.68      314330.153     1767608.216      313616.104
     1767963.376      313239.221
#Sta/Elev= 30
       0  1055.9    75.3 1048.03   208.8 1046.77   230.2 1043.97   264.1 1037.31
   327.6 1035.03   365.8 1031.35   501.5 1029.26   594.7 1029.12   639.2 1029.74
   674.1 1032.89   683.7 1032.52   713.4 1028.25   832.2 1027.98     890 1022.38
   891.6 1022.19     905 1023.59     942 1040.17   958.8 1046.58   978.4 1050.92
    1026 1058.91  1103.5 1063.82  1168.8 1061.54  1185.1 1062.36  1244.4 1082.26
  1299.3 1103.72  1328.4 1111.03    1342 1112.57  1359.3 1112.69  1410.4 1108.92
#Mann= 3 , 0 , 0
       0      .1       0     890    .045       0     905      .1       0
#XS Ineff= 2 , 0
          671.74 1033.45
Permanent Ineff=
       F       F
Bank Sta=890,905
XS Rating Curve= 0 ,0
Exp/Cntr=0.3,0.1

Type RM Length L Ch R = 1 ,20790.6 ,331.531,332.219,329.115
XS GIS Cut Line= 3
     1767163.686      314316.152      1767811.23      314029.132
      1768312.54      313901.716
#Sta/Elev= 30
       0 1054.01    31.2 1052.04    55.5 1051.24    74.6 1051.52   110.6 1054.31
   128.6 1054.76     174 1053.03   191.6 1052.05     226 1048.68   289.9  1039.3
   303.9 1037.87   319.2 1036.75   355.9 1035.33   394.8 1032.22   465.7 1029.03
     495 1029.18   571.7 1031.83   589.6 1031.51   641.4 1028.06   680.5 1026.27
   693.5 1024.67   704.5 1022.46   708.1 1022.18   718.9 1021.89   723.1 1021.89
   767.9 1023.13   809.2 1023.39   958.2 1027.81  1159.9 1035.77  1224.9 1039.26
#Mann= 3 , 0 , 0
       0      .1       0   708.1    .045       0   723.1      .1       0
#XS Ineff= 2 , 0
          576.62 1032.08
Permanent Ineff=
       F       F
Bank Sta=708.1,723.1
XS Rating Curve= 0 ,0
Exp/Cntr=0.3,0.1

Type RM Length L Ch R = 1 ,20458.4 ,400.734,400,399.12
XS GIS Cut Line= 3
     1767470.441      314498.274     1767944.363      314334.695
     1768407.998      314146.568
#Sta/Elev= 30
       0 1091.76    32.2 1087.35      95 1079.36   132.7 1075.34   157.8 1072.18
   184.9 1067.68   233.2 1058.84   245.7 1057.71   259.6 1057.35   268.9 1056.77
   278.2 1055.55   358.8 1039.79   380.9 1035.07   408.7 1028.66   427.6 1026.33
     465  1023.6   493.9 1021.06   501.4 1020.84   508.9 1020.86   593.4 1024.56
   613.3 1025.17   701.9 1025.28   753.1  1024.8   812.2 1025.69   842.8 1027.61
   894.6 1032.49   921.6 1034.06   932.5 1034.27   957.8 1034.12  1001.7 1032.66
#Mann= 3 , 0 , 0
       0      .1       0   493.9    .045       0   508.9      .1       0
Bank Sta=493.9,508.9
XS Rating Curve= 0 ,0
Exp/Cntr=0.3,0.1

Type RM Length L Ch R = 1 ,20058.4 ,378.992,391.089,404.528
XS GIS Cut Line= 3
     1767649.332      314866.049     1768135.136      314681.192
     1768906.804      314333.653
#Sta/Elev= 30
       0  1158.1    82.5 1136.94   146.1 1123.04   181.3 1112.35   354.5 1067.54
   374.7 1061.59   402.2 1051.81   411.4  1049.6   425.5 1048.62   438.2 1046.41
   463.6 1038.88   512.3 1021.92   514.4 1021.27   527.3  1020.7   548.7 1021.64
   644.5 1023.27   711.7 1022.34   764.2 1022.63   839.8 1027.18     905 1027.18
  1015.5    1030  1061.2 1030.44  1087.6 1031.73  1116.5 1032.25  1141.2 1033.77
  1177.1 1037.29  1217.5 1042.73  1243.5 1045.56  1308.6 1050.36  1365.7 1055.32
#Mann= 3 , 0 , 0
       0      .1       0   512.3    .045       0   527.3      .1       0
Bank Sta=512.3,527.3
XS Rating Curve= 0 ,0
Exp/Cntr=0.3,0.1

Type RM Length L Ch R = 1 ,19667.3 ,400.605,411.947,423.258
XS GIS Cut Line= 3
     1767660.796      314983.145     1768228.918      315078.124
     1768878.802      315005.698
#Sta/Elev= 30
       0 1140.91    78.6 1119.23   149.1 1100.89   162.9  1097.5     199 1089.97
   223.1 1084.14   295.3 1065.67   343.5 1054.07     376 1044.85   396.6 1039.57
   417.3 1035.15   439.8 1031.13   451.8 1029.58   475.9 1027.96     512 1019.96
   514.6 1019.74     524  1019.1   529.6 1019.47   560.1 1022.87   611.1 1025.27
   715.5 1032.04   751.4 1033.39   763.3 1033.43   787.2 1032.28   811.1 1033.31
   930.6 1045.91   966.4 1051.26   978.4 1052.38    1122 1053.51  1229.5 1059.71
#Mann= 3 , 0 , 0
       0      .1       0   514.6    .045       0   529.6      .1       0
Bank Sta=514.6,529.6
XS Rating Curve= 0 ,0
Exp/Cntr=0.3,0.1