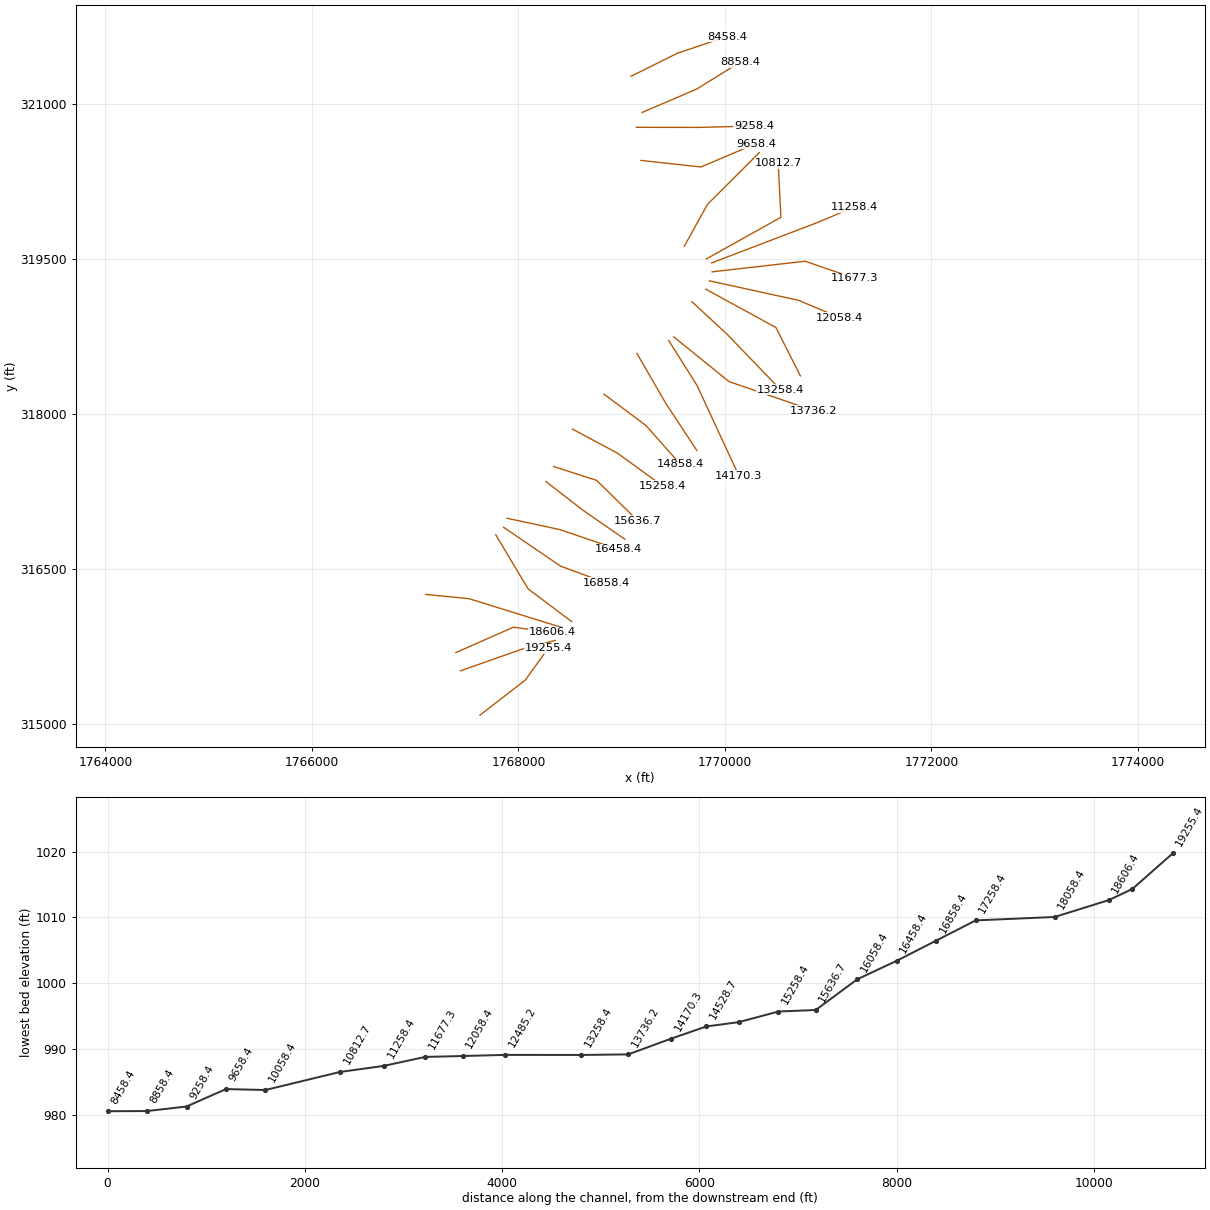
HEC-RAS study ThmasFk.prj: ThmasFk

--- ThmasFk.g01 (geometry) --- (continued)

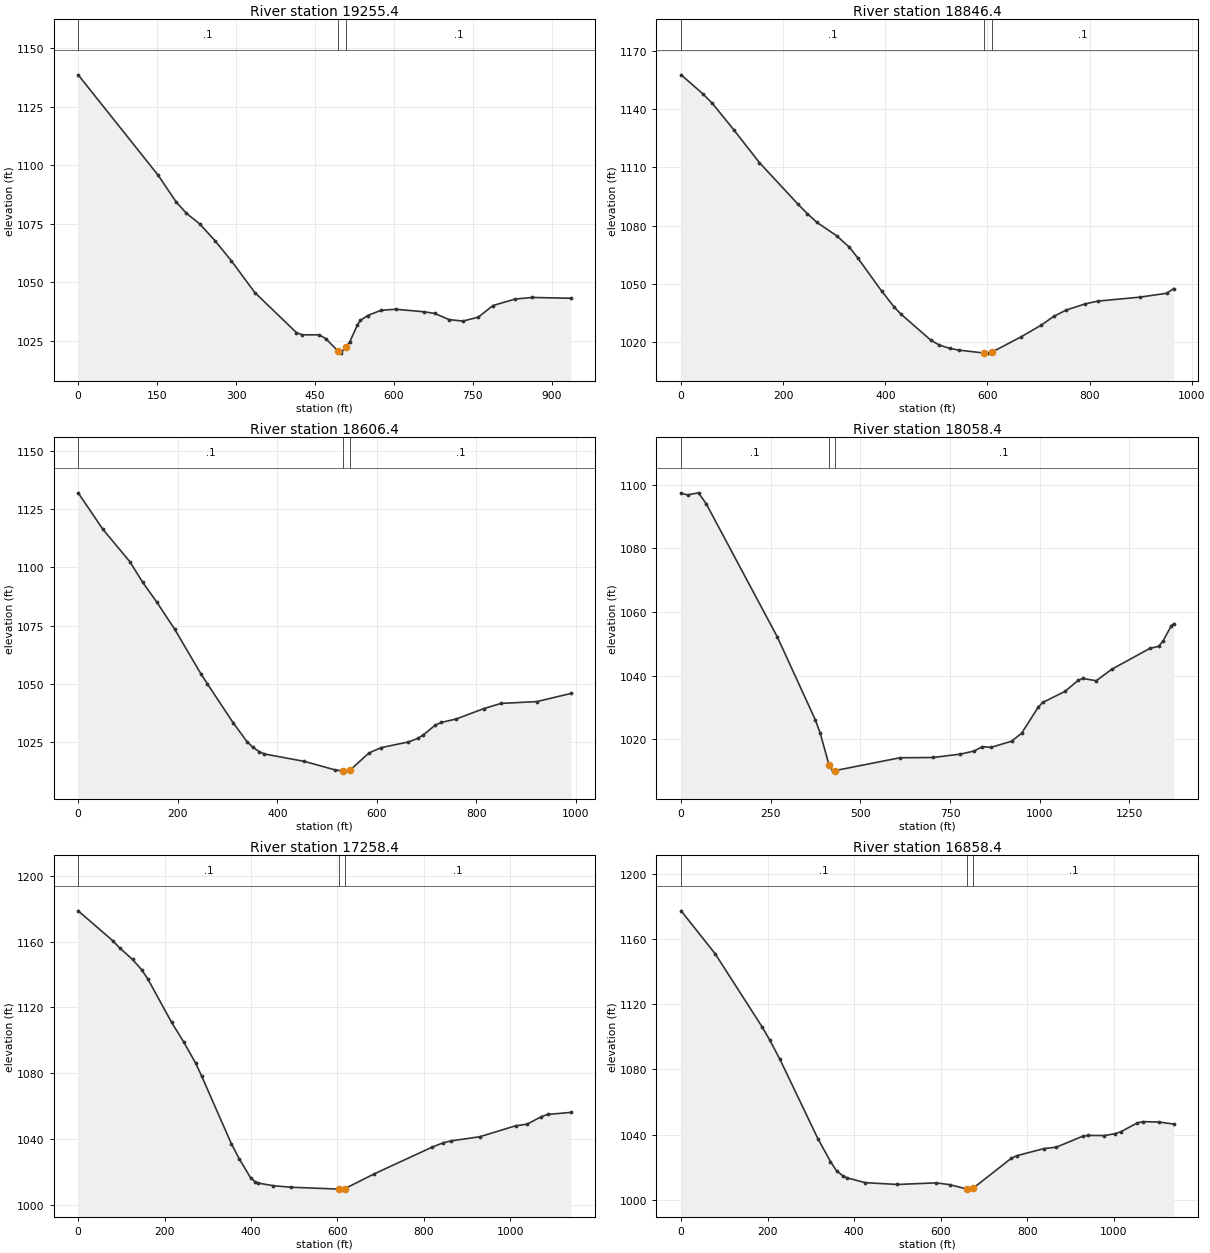
Type RM Length L Ch R = 1 ,19255.4 ,416.034,409.029,402.055
XS GIS Cut Line= 3
     1767627.092       315082.05     1768066.346       315421.33
     1768289.129      315730.417
#Sta/Elev= 30
       0 1138.71   152.1 1095.74   185.9 1084.44   205.8 1079.46   230.6 1075.05
   260.6 1067.62   290.6 1059.32   335.6 1045.63   414.5 1028.52   425.6 1027.54
   458.3 1027.55   470.6 1025.87   493.6 1020.64   499.1 1019.72   508.6 1022.37
   515.6 1024.33   530.6 1031.84     536 1033.69   549.9 1035.79   575.4 1038.04
   603.2 1038.48   657.8 1037.39   677.5 1036.67   704.7 1034.05     731 1033.43
   760.2  1035.1     788 1040.08   830.5 1042.85   862.7 1043.52   935.9 1043.18
#Mann= 3 , 0 , 0
       0      .1       0   493.6    .045       0   508.6      .1       0
Bank Sta=493.6,508.6
XS Rating Curve= 0 ,0
Exp/Cntr=0.3,0.1

Type RM Length L Ch R = 1 ,18846.4 ,238.163,239.953,241.744
XS GIS Cut Line= 3
       1767439.5      315511.658     1768030.219      315720.382
     1768357.369      315806.685
#Sta/Elev= 30
       0 1157.75    42.7 1147.94    61.3 1143.01   102.9 1129.51   153.3 1112.52
   228.5 1091.21   247.3 1086.18     266 1081.69   304.4 1074.86   329.5 1068.93
   345.8 1063.46   392.5 1046.39   417.7 1037.97   430.3 1034.48   489.3 1020.95
   505.8 1018.47   526.5 1016.75   543.6 1015.89     594 1014.33   600.9 1014.31
     609 1014.84   665.3 1022.62   705.3 1028.72   729.9 1033.25   754.4 1036.53
   791.3 1039.67   815.8 1041.11     898 1043.15   950.9 1045.15   964.9  1047.6
#Mann= 3 , 0 , 0
       0      .1       0     594    .045       0     609      .1       0
Bank Sta=594,609
XS Rating Curve= 0 ,0
Exp/Cntr=0.3,0.1

Type RM Length L Ch R = 1 ,18606.4 ,559.58,547.982,531.372
XS GIS Cut Line= 3
     1767393.983      315688.269      1767950.71      315934.002
     1768328.598      315884.092
#Sta/Elev= 30
       0 1131.92    49.9 1116.21   103.8 1102.41   129.8 1093.51   157.9  1085.1
     194 1073.41   246.6 1054.32   259.6 1050.04   311.5  1033.3   339.2 1025.26
   350.5 1022.93   363.4 1020.99     374 1019.98   454.3 1016.79   515.6 1013.17
   532.1 1012.64   536.1 1012.61   547.1 1013.22   584.1 1020.38   608.5 1022.68
   663.1  1025.1   681.8  1026.6   693.7 1028.17   717.7 1032.39   729.7 1033.48
   759.5 1034.97   814.9 1039.41   849.4 1041.64   921.3 1042.41   989.7  1045.9
#Mann= 3 , 0 , 0
       0      .1       0   532.1    .045       0   547.1      .1       0
Bank Sta=532.1,547.1
XS Rating Curve= 0 ,0
Exp/Cntr=0.3,0.1

Type RM Length L Ch R = 1 ,18058.4 ,821.91,800,793.824
XS GIS Cut Line= 3
     1767102.987      316252.039     1767521.288       316210.84
     1768431.516       315928.34
#Sta/Elev= 30
       0 1097.25    18.1 1096.75    48.5 1097.39    70.2 1093.92   268.6 1052.08
   374.3 1026.11   387.9 1021.91   412.8 1011.82   423.8 1010.05   427.8 1010.19
   610.3 1014.25   702.7 1014.33   778.5 1015.39   816.5 1016.34     840 1017.73
   863.9 1017.51   921.1 1019.43   949.3 1021.94   995.7 1030.13  1008.1 1031.59
  1070.3 1035.08  1107.6  1038.6  1120.1 1039.14  1157.3 1038.41  1200.5 1042.01
  1306.5 1048.55  1331.3 1049.23  1343.8 1050.94  1366.7 1055.69  1373.4 1056.29
#Mann= 3 , 0 , 0
       0      .1       0   412.8    .045       0   427.8      .1       0
Bank Sta=412.8,427.8
XS Rating Curve= 0 ,0
Exp/Cntr=0.3,0.1

Type RM Length L Ch R = 1 ,17258.4 ,390.434,400,403.632
XS GIS Cut Line= 3
     1767780.641      316830.184     1768093.691      316306.146
     1768517.251      315987.882
#Sta/Elev= 30
       0 1178.73    79.6 1160.67    95.9 1156.22   125.9 1149.18   147.2  1142.8
     161 1137.41   216.3 1110.89     244 1099.12   271.7 1086.21   285.5 1078.44
   354.6  1037.1     373 1027.93     399 1016.46     410 1013.92   416.3 1013.23
   451.4 1011.61   492.9 1010.69   602.9 1009.55   603.6 1009.53   617.9  1009.9
   685.7 1018.88     818 1034.91   844.2 1037.66   863.9  1038.9     929 1041.34
  1012.4 1048.04  1039.3 1049.03  1071.8 1053.57  1086.7 1054.95  1140.2 1056.17
#Mann= 3 , 0 , 0
       0      .1       0   602.9    .045       0   617.9      .1       0
Bank Sta=602.9,617.9
XS Rating Curve= 0 ,0
Exp/Cntr=0.3,0.1

Type RM Length L Ch R = 1 ,16858.4 ,393.37,400,396.255
XS GIS Cut Line= 3
     1767856.888       316902.44      1768408.28      316526.271
     1768850.245      316363.113
#Sta/Elev= 30
       0 1177.34    78.6 1151.03   187.1 1106.15     205 1097.95   228.5 1086.09
   316.4 1037.31   345.2 1023.42   359.5 1017.64   373.5 1014.72   382.3 1013.51
     425 1010.45   499.9 1009.32   589.5 1010.31   621.5 1009.17     660 1006.55
   664.2 1006.46     675 1007.03   763.3 1025.43     776    1027   839.3 1031.39
   867.3 1032.22   927.9 1038.93   940.5 1039.44   978.5 1039.35  1003.8 1040.56
  1016.5 1041.74  1054.4  1047.1  1067.1  1047.9    1105 1047.65  1138.6 1046.39
#Mann= 3 , 0 , 0
       0      .1       0     660    .045       0     675      .1       0
Bank Sta=660,675
XS Rating Curve= 0 ,0
Exp/Cntr=0.3,0.1

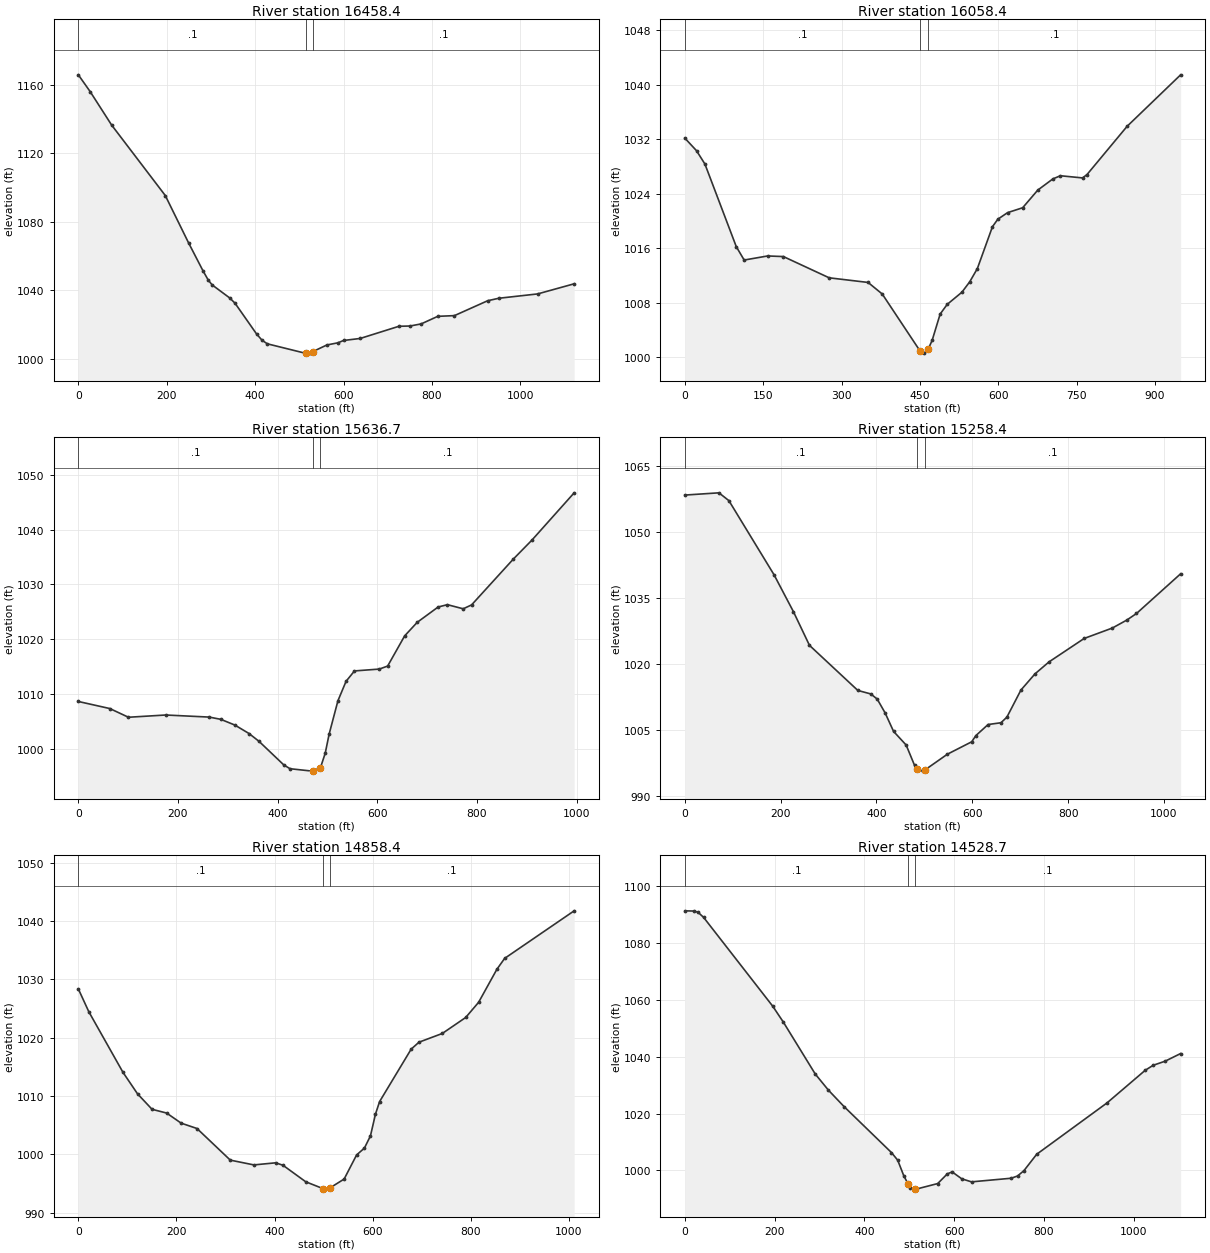
Type RM Length L Ch R = 1 ,16458.4 ,408.424,400,397.629
XS GIS Cut Line= 3
     1767890.318      316989.602      1768401.62      316880.065
     1768968.266      316687.245
#Sta/Elev= 30
       0 1165.81    26.7 1156.04    75.3  1136.5   196.7 1095.36   249.2 1067.82
   281.7 1051.57   293.8 1046.04   302.7  1043.2   342.4 1035.59   354.5  1032.5
   403.1 1014.59   415.3 1010.98   427.4 1008.83   512.4 1003.39   515.4 1003.43
   524.6 1003.48   530.4 1004.29   562.2 1008.15   587.3 1009.42   599.8 1010.77
   637.5 1011.95   725.2 1019.06   750.3 1019.22   775.4 1020.44     813 1024.86
   850.7 1025.28   925.9 1033.97     951 1035.41  1038.8 1037.94  1121.5 1043.85
#Mann= 3 , 0 , 0
       0      .1       0   515.4    .045       0   530.4      .1       0
Bank Sta=515.4,530.4
XS Rating Curve= 0 ,0
Exp/Cntr=0.3,0.1

Type RM Length L Ch R = 1 ,16058.4 ,419.796,421.735,424.158
XS GIS Cut Line= 3
     1768265.876      317345.886     1768628.304      317065.486
      1769031.74      316786.128
#Sta/Elev= 30
       0 1032.16    22.4 1030.31    38.5 1028.35    98.5 1016.22   113.6 1014.25
   158.6 1014.85   188.7 1014.76   276.3 1011.64   350.8 1010.96   377.9 1009.26
   450.7 1000.84   458.2 1000.58   465.7 1001.15   473.3 1002.44   488.7 1006.32
   502.2 1007.74   530.4 1009.53   545.5 1011.08   559.9    1013   588.8 1019.15
   599.1 1020.25   617.7 1021.21   646.6 1021.93   675.5 1024.52   704.3 1026.16
   718.8 1026.63   761.2 1026.31   769.7  1026.8   846.5 1033.89   948.9 1041.45
#Mann= 3 , 0 , 0
       0      .1       0   450.7    .045       0   465.7      .1       0
Bank Sta=450.7,465.7
XS Rating Curve= 0 ,0
Exp/Cntr=0.3,0.1

Type RM Length L Ch R = 1 ,15636.7 ,375.237,378.265,375.959
XS GIS Cut Line= 3
     1768343.075      317490.558     1768758.077      317356.498
     1769157.643      316964.796
#Sta/Elev= 30
       0 1008.62    63.2 1007.33   100.6 1005.74   175.5 1006.15   262.8 1005.77
     286 1005.36   314.3 1004.31   342.6 1002.77   362.6 1001.35   412.6  997.02
     425  996.34   469.6   995.9   470.9  995.94   485.9  996.49   495.6  999.17
   503.5 1002.68   521.1 1008.75   537.4  1012.3   554.3  1014.2   604.2 1014.54
   620.9 1015.09   655.1 1020.61   680.3 1023.08   722.3 1025.88   740.9  1026.3
   772.6 1025.55   789.4 1026.26   873.4 1034.65   910.5 1038.09   995.3 1046.73
#Mann= 3 , 0 , 0
       0      .1       0   470.9    .045       0   485.9      .1       0
Bank Sta=470.9,485.9
XS Rating Curve= 0 ,0
Exp/Cntr=0.3,0.1

Type RM Length L Ch R = 1 ,15258.4 ,402.844,400,395.515
XS GIS Cut Line= 3
     1768523.929      317853.422     1768958.606      317621.082
     1769397.167      317302.688
#Sta/Elev= 30
       0 1058.33    71.2 1058.84      92 1057.07   186.2 1040.25   226.6 1031.89
   260.2 1024.22   361.2 1013.98   388.2 1013.19   401.6 1012.02   418.1 1008.88
   435.7 1004.69     462 1001.59   479.5  996.98   485.4  996.17   496.1  995.67
   500.4  995.88     548  999.51   598.8 1002.33   607.5 1003.74     633 1006.25
   659.8 1006.65   672.2 1007.92   701.5 1014.07   730.9 1017.75   760.2 1020.47
   833.6 1025.79   892.3 1028.15   922.5 1029.96   942.7 1031.45  1034.8 1040.46
#Mann= 3 , 0 , 0
       0      .1       0   485.4    .045       0   500.4      .1       0
Bank Sta=485.4,500.4
XS Rating Curve= 0 ,0
Exp/Cntr=0.3,0.1

Type RM Length L Ch R = 1 ,14858.4 ,338.977,329.773,325.439
XS GIS Cut Line= 3
      1768828.98      318192.472     1769234.146       317889.52
      1769569.51      317512.065
#Sta/Elev= 30
       0 1028.37    21.4 1024.46      91 1014.08   120.7 1010.39   150.3 1007.74
     180  1007.1   209.6 1005.37   241.9 1004.45   309.8  999.03   357.9  998.21
   402.3  998.57   417.2  998.15   463.6  995.32   498.4  994.16   503.3  994.06
   513.4  994.29   541.9  995.79   567.3  999.92   583.2 1001.09   595.5 1003.18
   605.8 1006.93   614.2 1009.07   678.5 1018.05   694.4 1019.24     742 1020.74
   789.7 1023.48   816.1 1026.09   853.2 1031.73   869.1 1033.61  1010.8 1041.76
#Mann= 3 , 0 , 0
       0      .1       0   498.4    .045       0   513.4      .1       0
Bank Sta=498.4,513.4
XS Rating Curve= 0 ,0
Exp/Cntr=0.3,0.1

Type RM Length L Ch R = 1 ,14528.7 ,357.383,358.357,356.447
XS GIS Cut Line= 3
     1769148.149      318586.456     1769429.137      318100.749
     1769728.188      317647.154
#Sta/Elev= 30
       0 1091.36    21.5 1091.28    29.8 1090.81    41.9 1089.05   195.8  1057.8
   219.5 1052.19   290.6 1033.91     320 1028.22   354.7 1022.46   460.4 1006.26
   474.2 1003.59   487.9  998.05   497.3  995.24   501.6  993.89   512.3  993.46
   515.3   993.4   563.3  995.36   584.7  998.76   595.4  999.47     617  997.02
   638.6  995.96   726.9  997.23   741.1  998.02   755.4   999.9   783.8 1005.67
   940.4 1023.74  1025.6 1035.24  1043.2 1036.99    1070 1038.44  1104.4 1041.13
#Mann= 3 , 0 , 0
       0      .1       0   497.3    .045       0   512.3      .1       0
Bank Sta=497.3,512.3
XS Rating Curve= 0 ,0
Exp/Cntr=0.3,0.1

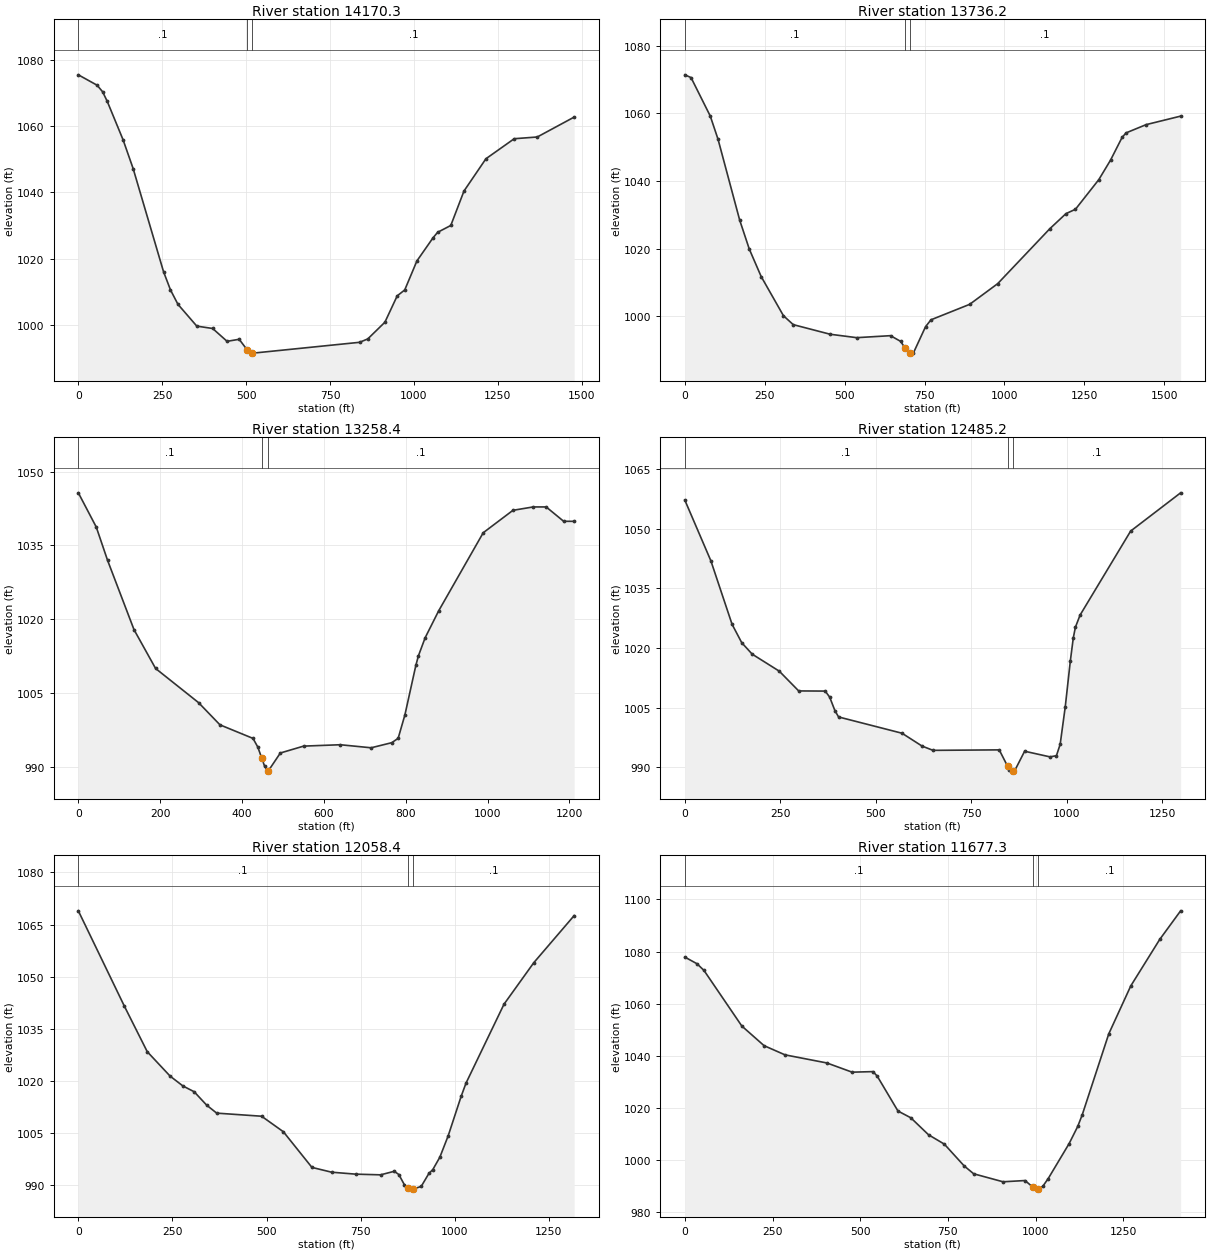
Type RM Length L Ch R = 1 ,14170.3 ,423.575,434.055,454.081
XS GIS Cut Line= 3
     1769455.848      318712.072      1769729.36       318278.42
     1770135.388      317403.361
#Sta/Elev= 30
       0 1075.43    55.9  1072.3    72.3 1070.33    86.3  1067.4   133.3 1055.85
   163.4 1047.14   253.8 1016.11   274.6 1010.59   296.9 1006.24     353  999.68
   400.2  998.97   443.2   995.1   479.3  995.71   503.8  992.43   518.8  991.55
   520.9  991.54     838   994.8   862.4  995.82   913.5 1000.86   950.1  1008.8
   972.6 1010.59  1008.9 1019.34  1057.2 1026.34  1070.6 1027.96  1109.8 1030.02
  1149.1  1040.4  1214.5 1050.13  1298.8 1056.17  1367.5 1056.69  1477.4 1062.69
#Mann= 3 , 0 , 0
       0      .1       0   503.8    .045       0   518.8      .1       0
Bank Sta=503.8,518.8
XS Rating Curve= 0 ,0
Exp/Cntr=0.3,0.1

Type RM Length L Ch R = 1 ,13736.2 ,477.919,477.815,467.129
XS GIS Cut Line= 3
     1769504.788      318747.069     1770040.881      318313.422
     1770856.436      318033.403
#Sta/Elev= 30
       0 1071.42    19.5 1070.61    79.7 1059.23     104 1052.37   171.7 1028.48
   201.8  1019.9     239 1011.78   308.7  1000.2   339.3  997.57   454.9  994.73
   537.8  993.72   643.7  994.31   675.2  992.63   688.3  990.77   702.9  989.15
   703.3  989.16   715.4  989.23   753.1  996.94   770.2     999   891.2 1003.57
     979 1009.69  1142.2 1025.94  1192.5 1030.38  1222.3 1031.68  1295.4 1040.45
    1332  1046.2  1368.2 1052.93  1380.7 1054.26  1443.5  1056.7  1551.3 1059.21
#Mann= 3 , 0 , 0
       0      .1       0   688.3    .045       0   703.3      .1       0
Bank Sta=688.3,703.3
XS Rating Curve= 0 ,0
Exp/Cntr=0.3,0.1

Type RM Length L Ch R = 1 ,13258.4 ,781.608,773.18,766.053
XS GIS Cut Line= 3
     1769680.446      319087.706     1770015.012      318778.876
     1770540.391      318234.491
#Sta/Elev= 30
       0 1045.69    43.8 1038.73    71.5 1031.94   136.1 1017.84   188.8 1009.95
   293.9 1002.99   346.1  998.48   426.9  995.72   438.7  993.94   447.8  991.79
   455.3  990.05   462.8  989.17   463.9  989.06   493.7  992.75   550.6  994.15
   640.2  994.43   715.6  993.81   766.1  994.85   781.6  995.74   798.1 1000.51
   824.9  1010.6   831.1 1012.52   847.6 1016.21   880.6 1021.68   989.5 1037.57
  1062.1 1042.13  1111.6 1042.82  1143.3 1042.82    1186  1039.9  1211.7 1039.89
#Mann= 3 , 0 , 0
       0      .1       0   447.8    .045       0   462.8      .1       0
Bank Sta=447.8,462.8
XS Rating Curve= 0 ,0
Exp/Cntr=0.3,0.1

Type RM Length L Ch R = 1 ,12485.2 ,405.997,426.82,443.343
XS GIS Cut Line= 3
     1769815.523      319208.994     1770494.883      318837.338
     1770731.353      318369.398
#Sta/Elev= 30
       0 1057.18    68.3 1041.91   123.8 1025.96   149.1 1021.34   176.5 1018.46
   247.5 1014.18   298.3 1009.22   367.8 1009.18   379.5 1007.66   393.1 1004.29
   402.8 1002.68     569  998.59   621.5  995.36   650.2  994.29   823.6  994.41
   845.4  990.31   850.2  989.26   860.4  989.12   863.5  989.07   890.1  994.07
   956.6  992.65   973.4  992.95   983.2  995.81   996.5 1005.21  1009.8 1016.73
  1017.6 1022.56  1023.1 1025.22  1035.3 1028.27  1167.8 1049.38  1298.7 1058.99
#Mann= 3 , 0 , 0
       0      .1       0   845.4    .045       0   860.4      .1       0
Bank Sta=845.4,860.4
XS Rating Curve= 0 ,0
Exp/Cntr=0.3,0.1

Type RM Length L Ch R = 1 ,12058.4 ,383.914,381.084,382.534
XS GIS Cut Line= 3
     1769850.859      319289.564     1770712.901      319101.313
     1771114.085      318933.298
#Sta/Elev= 30
       0 1068.95   122.4 1041.51   183.1 1028.43   243.9  1021.4   277.9 1018.57
   307.8 1016.91   341.1 1013.04   367.6 1010.76   486.9 1009.87   544.8  1005.4
   620.6  995.15   672.9  993.77   736.7  993.21   802.9  993.01   839.4  994.03
   851.5   993.1   866.4  990.13   874.9  989.17   888.3   988.9   889.9  988.91
   911.1   989.7   931.3   993.4   941.8  994.53   960.5  998.09   982.6 1004.23
    1017 1015.57  1029.9 1019.37  1130.9 1042.09  1210.1 1054.04  1317.3 1067.58
#Mann= 3 , 0 , 0
       0      .1       0   874.9    .045       0   889.9      .1       0
Bank Sta=874.9,889.9
XS Rating Curve= 0 ,0
Exp/Cntr=0.3,0.1

Type RM Length L Ch R = 1 ,11677.3 ,403.192,418.916,435.39
XS GIS Cut Line= 3
     1769876.596      319376.968     1770777.878      319479.596
     1771256.305      319314.822
#Sta/Elev= 30
       0 1077.88    34.7 1075.32    54.7 1072.75   162.5  1051.4   225.9 1043.86
   285.6 1040.33     405 1037.21   476.8 1033.68   536.5 1033.89   548.5 1032.14
   607.5 1018.76   644.1 1016.16   694.6 1009.64   739.7 1006.04   796.3  997.66
   823.3  994.65     907  991.58   969.7  992.06   992.9  989.41  1007.4  988.76
  1007.9  988.79    1020  989.78  1035.8  992.83  1095.3 1006.24  1119.9 1012.85
    1133 1017.42  1208.3 1048.39  1271.1 1066.82  1353.4 1084.63  1413.1 1095.64
#Mann= 3 , 0 , 0
       0      .1       0   992.9    .045       0  1007.9      .1       0
Bank Sta=992.9,1007.9
XS Rating Curve= 0 ,0
Exp/Cntr=0.3,0.1

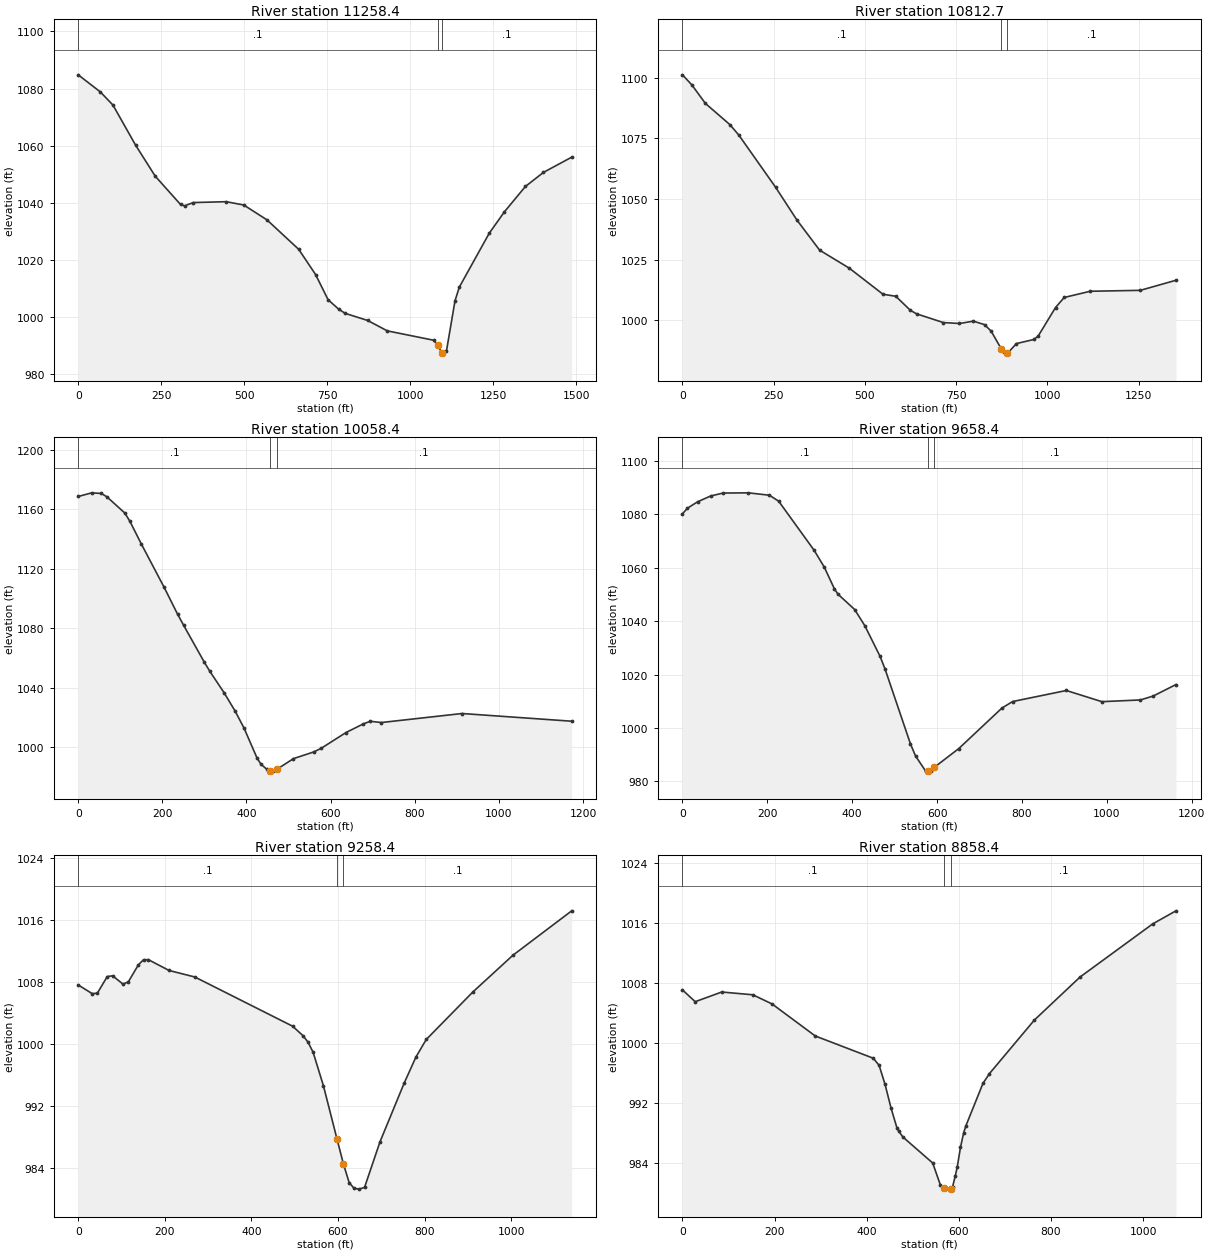
Type RM Length L Ch R = 1 ,11258.4 ,417.242,445.754,473.536
XS GIS Cut Line= 3
     1769872.566      319463.402     1770890.376      319852.112
     1771256.056      320005.541
#Sta/Elev= 30
       0  1084.8    66.6 1078.82   104.7  1074.2     173 1060.15   231.8 1049.35
   308.1 1039.42   320.1 1038.93   346.2 1040.09   445.6  1040.4   498.7 1039.23
   568.4 1034.04   663.9 1023.74   714.8 1014.91   752.4  1006.1   784.3 1002.79
   803.7 1001.33   871.9  998.82   930.8  995.19  1070.6  991.91    1082  990.16
  1096.1   987.4    1097  987.47    1109  988.18  1134.7 1005.72  1147.6 1010.49
  1237.7 1029.35  1283.1  1036.8  1346.6 1045.72    1401 1050.65  1486.1 1055.98
#Mann= 3 , 0 , 0
       0      .1       0    1082    .045       0    1097      .1       0
Bank Sta=1082,1097
XS Rating Curve= 0 ,0
Exp/Cntr=0.3,0.1

Type RM Length L Ch R = 1 ,10812.7 ,766.589,754.246,735.263
XS GIS Cut Line= 3
     1769820.478      319501.768     1770543.052      319905.091
      1770516.96      320428.933
#Sta/Elev= 30
       0 1101.13    25.9 1096.95    62.9 1089.34     130 1080.61   154.4 1076.31
   255.2 1054.81   313.8 1041.26   375.7 1028.91   457.2 1021.46   549.4 1010.73
   584.4  1009.9   624.4 1004.11   641.6 1002.65   714.6  999.07   758.9  998.68
   797.2  999.64   827.5  998.21   845.6  995.56     874  988.08   879.6  986.84
     889  986.53   890.9  986.47   915.1  990.41   962.6  992.09   974.5  993.49
  1022.1 1005.25  1045.8  1009.4  1117.2 1011.96  1254.5 1012.34    1352 1016.49
#Mann= 3 , 0 , 0
       0      .1       0     874    .045       0     889      .1       0
Bank Sta=874,889
XS Rating Curve= 0 ,0
Exp/Cntr=0.3,0.1

Type RM Length L Ch R = 1 ,10058.4 ,426.809,400,392.36
XS GIS Cut Line= 3
     1769606.857      319623.799     1769831.503      320030.291
     1770332.933      320531.235
#Sta/Elev= 30
       0 1168.73    32.1  1171.2    55.1 1170.77    68.6 1168.42   110.8 1157.59
   122.9    1152     150 1136.76   204.3 1107.54   236.1 1089.51   250.6 1081.99
   299.2  1057.4   312.8 1051.01   346.7 1036.59   372.9 1024.25   394.2 1012.72
   425.3  992.44   434.9  988.23   448.4  984.98   456.9  983.96     462  983.73
   471.9  984.89   511.8  992.16   560.1  996.67   577.9  999.14   636.7 1009.75
   677.6 1015.52   694.3  1017.3   720.7 1016.47   912.5 1022.54  1173.2 1017.35
#Mann= 3 , 0 , 0
       0      .1       0   456.9    .045       0   471.9      .1       0
Bank Sta=456.9,471.9
XS Rating Curve= 0 ,0
Exp/Cntr=0.3,0.1

Type RM Length L Ch R = 1 ,9658.4  ,397.593,400,390.49
XS GIS Cut Line= 3
     1769186.957       320456.19     1769769.211      320392.673
     1770300.836      320619.385
#Sta/Elev= 30
       0 1080.14    11.8 1082.24    35.7 1084.64    66.2 1086.79    95.4  1087.9
   155.1 1087.99     205 1087.09   226.8 1084.85   310.4 1066.47   334.3 1060.17
   358.1 1052.05   366.5 1050.07   405.9 1044.32   429.8 1038.26   465.6 1026.83
   477.6 1021.98   537.3  994.06   549.2  989.55   573.1  983.87   578.2  983.99
   585.1  983.95   593.2  985.26   651.3  992.33   752.8 1007.46   777.9  1009.9
   904.6 1014.04   988.2 1009.86    1079  1010.5  1109.3 1011.96  1162.9 1016.26
#Mann= 3 , 0 , 0
       0      .1       0   578.2    .045       0   593.2      .1       0
Bank Sta=578.2,593.2
XS Rating Curve= 0 ,0
Exp/Cntr=0.3,0.1

Type RM Length L Ch R = 1 ,9258.4  ,390.728,400,412.055
XS GIS Cut Line= 3
     1769142.723      320776.885     1769748.024       320775.94
     1770282.566       320789.64
#Sta/Elev= 30
       0 1007.61    32.2 1006.49    44.1 1006.54    67.2  1008.7    79.7 1008.79
   103.5 1007.71   115.9 1008.02   139.1 1010.22   150.9 1010.87   162.3 1010.87
   209.9 1009.48   269.3 1008.64   495.2 1002.28   519.1 1001.06   530.9 1000.22
   542.7   998.9   566.6  994.55   597.8   987.7   612.8  984.44   625.9  982.07
   637.1  981.33   648.7  981.22   661.5  981.45   697.1  987.33   752.9  994.91
   780.3  998.31     804 1000.56   910.9 1006.66    1004 1011.44    1140 1017.19
#Mann= 3 , 0 , 0
       0      .1       0   597.8    .045       0   612.8      .1       0
Bank Sta=597.8,612.8
XS Rating Curve= 0 ,0
Exp/Cntr=0.3,0.1

Type RM Length L Ch R = 1 ,8858.4  ,398.582,400,394.925
XS GIS Cut Line= 3
     1769198.015      320920.645     1769726.298      321146.839
     1770148.838      321408.418
#Sta/Elev= 30
       0 1007.08    27.7 1005.51    85.3  1006.8   152.7 1006.43   194.5 1005.21
   288.3 1000.94     414  997.98   426.9  997.03   439.8  994.48   452.8  991.33
   465.7  988.67   469.2  988.27   478.6  987.47   543.2  984.01   559.6  981.13
   567.2  980.64     569  980.53   582.2  980.56   586.2   980.8   592.2  982.29
   596.5  983.47   603.5   986.1   610.4  988.03   614.8   988.9   652.3  994.62
   666.3  995.92     764 1003.07   862.9 1008.79  1020.8 1015.88  1071.2 1017.62
#Mann= 3 , 0 , 0
       0      .1       0   567.2    .045       0   582.2      .1       0
Bank Sta=567.2,582.2
XS Rating Curve= 0 ,0
Exp/Cntr=0.3,0.1

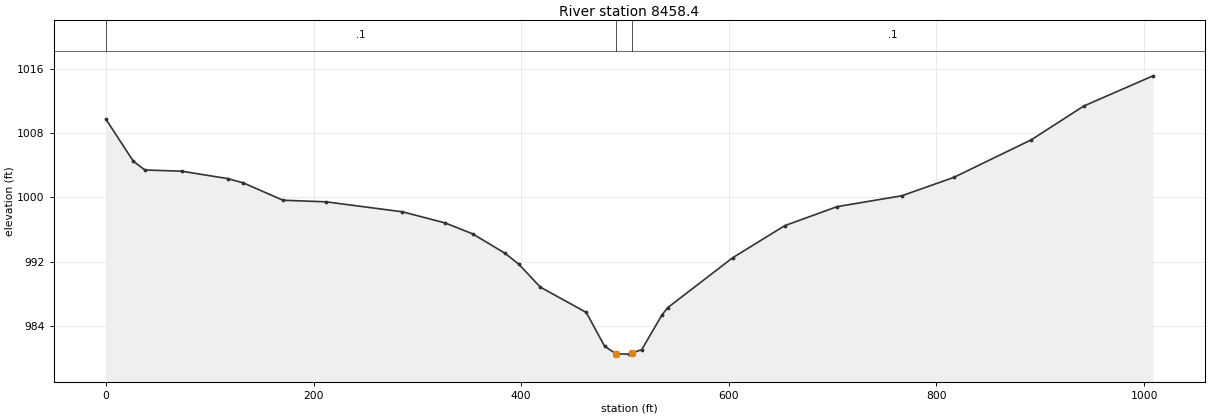
Type RM Length L Ch R = 1 ,8458.4  ,286.055,286.675,282.484
XS GIS Cut Line= 3
     1769091.896      321271.784     1769538.653      321493.976
     1770021.779      321656.456
#Sta/Elev= 30
       0 1009.72    26.4 1004.49    37.6  1003.4      73 1003.25   117.3 1002.33
   132.5 1001.79   170.5  999.64   212.1  999.44   285.6   998.2   326.7  996.82
   353.4  995.45   384.5  993.04   397.7  991.69   418.4  988.84   462.7  985.69
   480.4  981.48   491.5  980.53   503.5   980.5   506.5  980.64   516.1  981.05
   535.6  985.36   541.1  986.27   603.7  992.48   653.8  996.47   704.3  998.84
   766.6 1000.19   816.8 1002.48   891.5 1007.16   941.9 1011.35  1008.7 1015.11
#Mann= 3 , 0 , 0
       0      .1       0   491.5    .045       0   506.5      .1       0
Bank Sta=491.5,506.5
XS Rating Curve= 0 ,0
Exp/Cntr=0.3,0.1