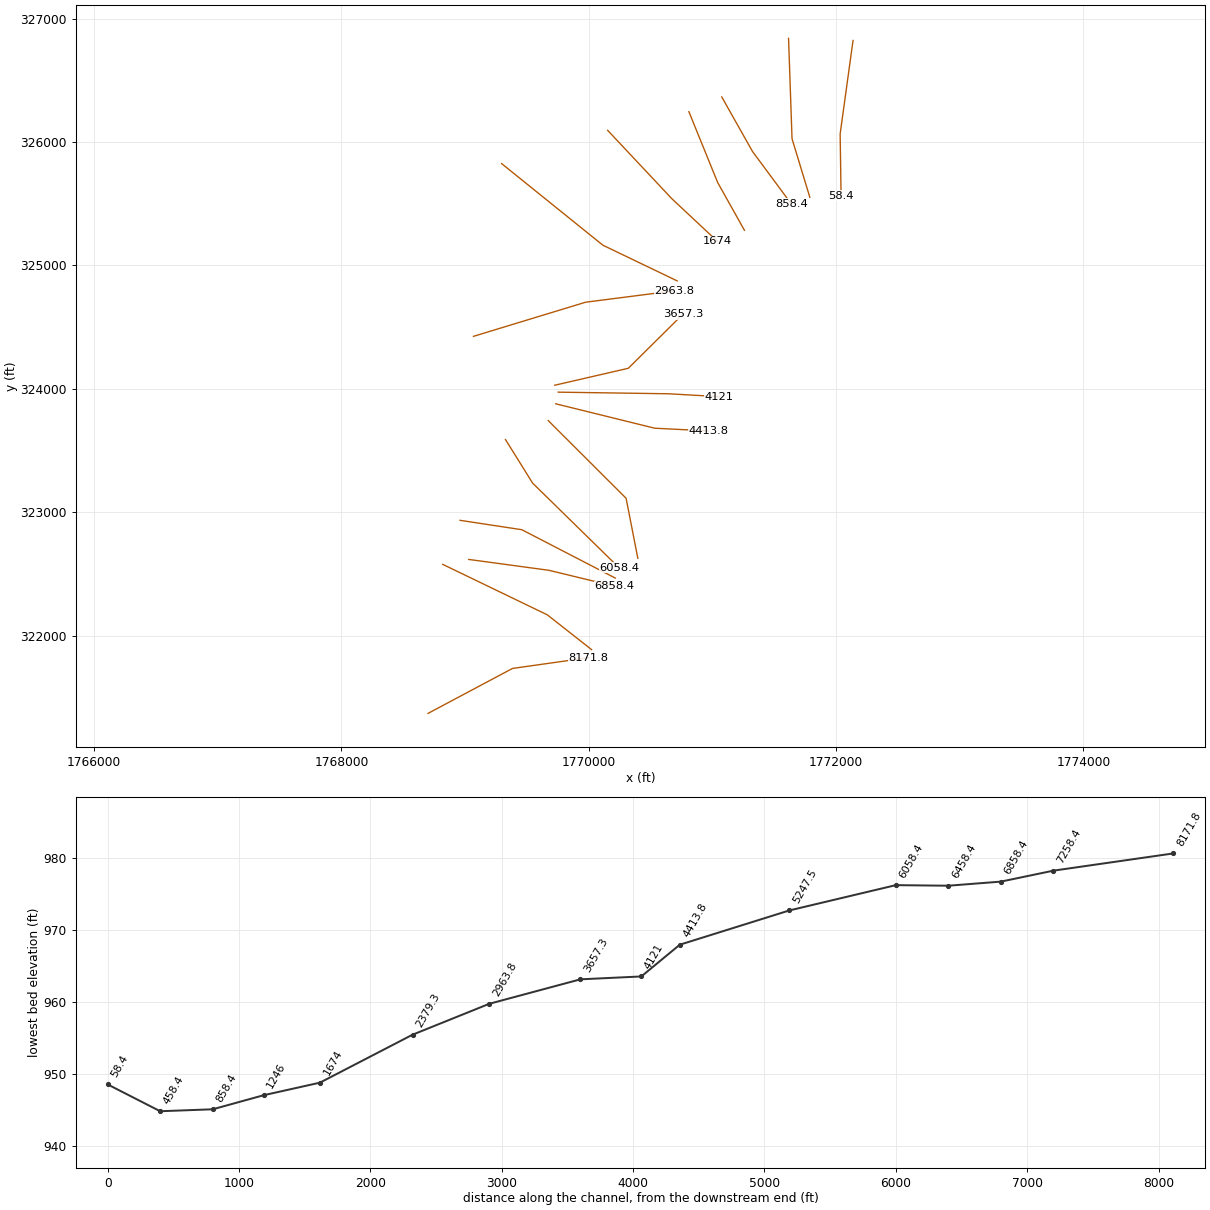
HEC-RAS study ThmasFk.prj: ThmasFk

--- ThmasFk.g01 (geometry) --- (continued)

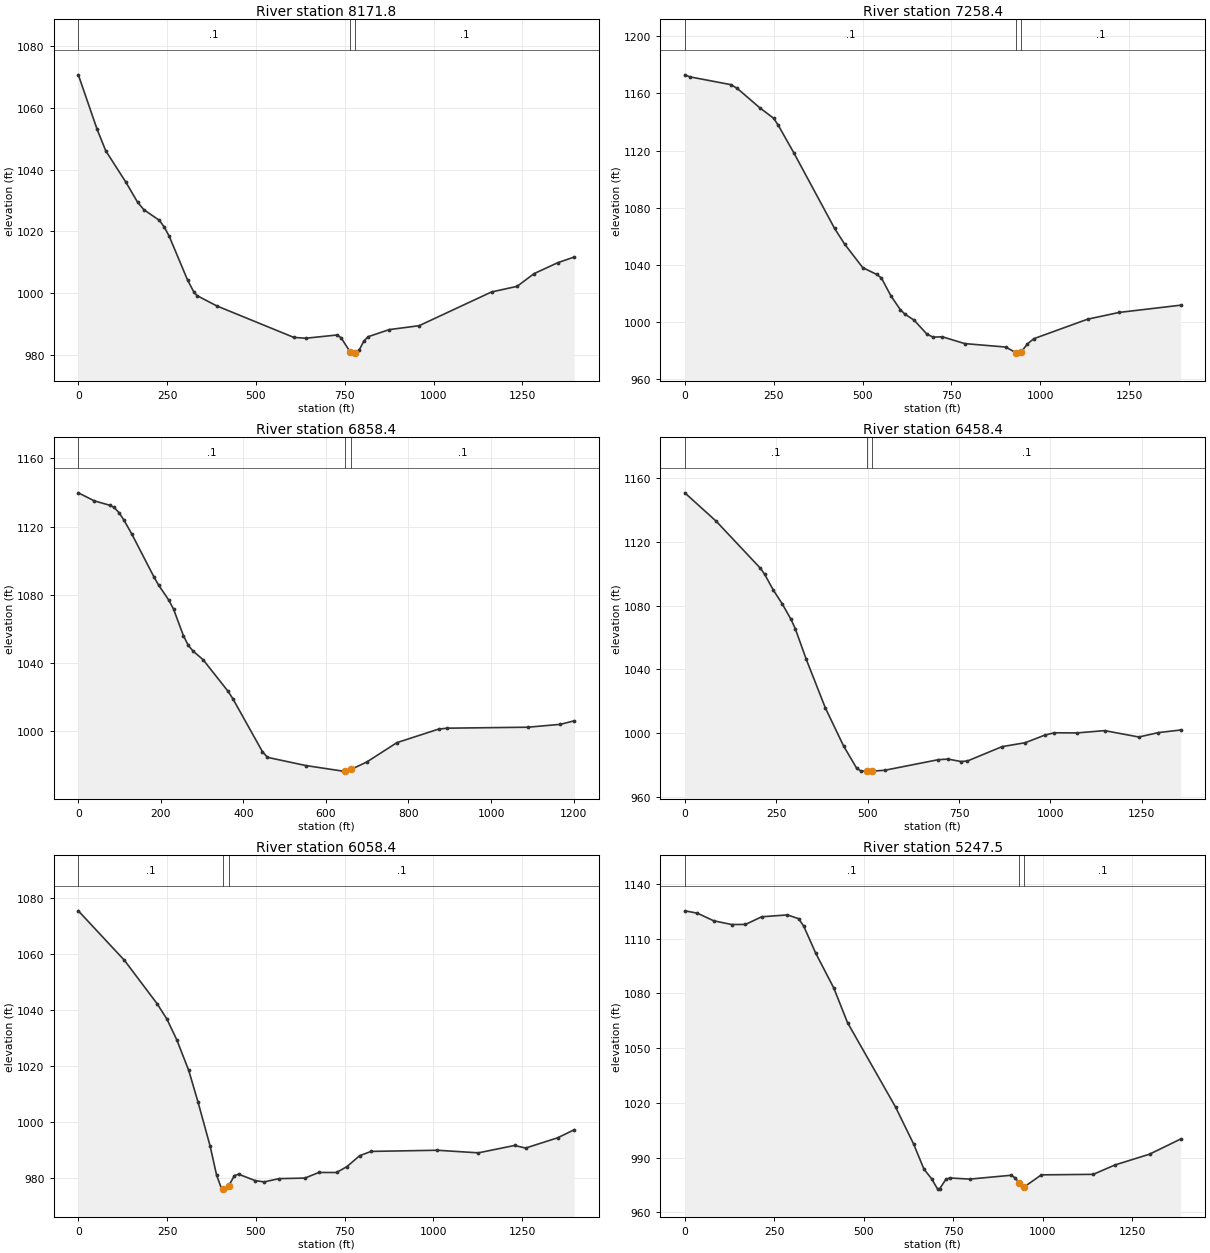
Type RM Length L Ch R = 1 ,8171.8  ,932.69,913.325,895.263
XS GIS Cut Line= 3
      1768700.29      321369.129     1769382.837      321733.154
     1769998.878       321820.66
#Sta/Elev= 30
       0  1070.7    52.9 1053.05    77.1 1046.13   134.3 1035.85     167 1029.42
   184.6 1027.02   228.4 1023.57   241.9  1021.4   255.4 1018.55   307.4 1004.28
     325 1000.44   333.8  999.24   389.9  995.87   606.9  985.67   640.9  985.42
   728.6  986.47   739.8  985.55     765  981.01   779.4  980.59     780  980.61
   791.4  981.76   803.4  984.42   815.4  985.89   875.4  988.21   959.3  989.47
  1163.2  1000.4  1235.1 1002.21  1283.1 1006.34  1349.8 1009.88  1395.8  1011.7
#Mann= 3 , 0 , 0
       0      .1       0     765    .045       0     780      .1       0
Bank Sta=765,780
XS Rating Curve= 0 ,0
Exp/Cntr=0.3,0.1

Type RM Length L Ch R = 1 ,7258.4  ,394.867,400,408.978
XS GIS Cut Line= 3
     1768819.298      322576.711     1769665.055       322167.68
     1770022.982      321885.768
#Sta/Elev= 30
       0 1173.07    14.3 1171.65   129.9 1166.18   147.7 1163.56   210.4  1150.1
     250 1142.64   263.3 1137.63   307.7 1118.03   421.4 1065.55   449.9 1054.48
   500.6 1038.09   540.1 1033.28   553.3 1030.81   579.7 1018.41   606.1 1008.74
   618.8 1005.63   645.6 1001.18     681  991.57   698.4  989.41   724.8  989.63
   787.7  984.87   903.2  982.46     932  978.44   935.8   978.2     947  979.17
   964.2  984.68   981.8  988.28  1133.3 1001.96  1222.4 1006.71  1395.1 1011.76
#Mann= 3 , 0 , 0
       0      .1       0     932    .045       0     947      .1       0
Bank Sta=932,947
XS Rating Curve= 0 ,0
Exp/Cntr=0.3,0.1

Type RM Length L Ch R = 1 ,6858.4  ,400.344,400,386.02
XS GIS Cut Line= 3
     1769029.568      322616.765     1769677.921      322528.676
     1770209.527      322399.526
#Sta/Elev= 30
       0 1139.84    38.9 1135.11    76.7 1132.52    86.8 1131.25    98.8 1128.15
   110.8 1123.71   129.5  1115.7   182.7 1090.78   194.6 1085.71   218.6 1077.16
   230.6 1071.75   254.5 1056.17   266.5 1050.36   278.5 1046.98   302.5 1041.97
   362.4  1023.6   374.4 1019.15   445.9  988.17   458.2  984.76   551.4  979.95
   640.8  976.68   646.8  976.76   661.8  977.81   698.7     982     772  993.39
     873 1001.32   894.2 1001.86  1089.2 1002.43  1167.9 1004.11  1201.4 1006.16
#Mann= 3 , 0 , 0
       0      .1       0   646.8    .045       0   661.8      .1       0
Bank Sta=646.8,661.8
XS Rating Curve= 0 ,0
Exp/Cntr=0.3,0.1

Type RM Length L Ch R = 1 ,6458.4  ,419.335,400,402.585
XS GIS Cut Line= 3
     1768959.308      322933.735     1769458.839      322857.621
     1770214.389      322465.922
#Sta/Elev= 30
       0 1150.93      86 1133.07   206.1 1103.73   218.1 1099.91   242.1 1089.86
   266.2 1081.31   290.7 1071.37   302.2 1065.58   332.3 1046.33   384.5 1015.82
   434.3  991.95   470.3  977.87   482.3  976.19   494.3  976.11   497.8  976.11
   512.8  976.11   546.6  976.64   693.7  983.31   720.4  983.67   755.5  982.14
   773.1  982.48   867.6  991.47   931.6  993.99   984.5  998.72  1010.9 1000.21
  1072.5  1000.1  1148.4 1001.56    1242  997.55  1295.5 1000.31  1356.3 1001.95
#Mann= 3 , 0 , 0
       0      .1       0   497.8    .045       0   512.8      .1       0
Bank Sta=497.8,512.8
XS Rating Curve= 0 ,0
Exp/Cntr=0.3,0.1

Type RM Length L Ch R = 1 ,6058.4  ,818.761,810.939,797.594
XS GIS Cut Line= 3
     1769326.698      323588.147      1769546.24      323235.095
     1770246.126      322548.315
#Sta/Elev= 30
       0 1075.27   129.9 1057.64   221.6 1042.24   249.5 1036.72   277.5 1029.27
   310.9 1018.45   336.8  1007.3   371.2  991.49   389.3   981.2   403.3  976.35
   408.2  976.26   414.3  976.19   423.2  977.25   439.6  981.03   451.5   981.5
   498.3  979.21   523.5  978.77   565.5  979.93     638  980.12   677.3  982.12
   727.2  982.11   756.6  984.23   792.2  988.09   824.5  989.62  1010.9  990.03
  1126.5  989.11  1228.7  991.74  1259.5  990.81  1349.9  994.47  1396.3  997.32
#Mann= 3 , 0 , 0
       0      .1       0   408.2    .045       0   423.2      .1       0
Bank Sta=408.2,423.2
XS Rating Curve= 0 ,0
Exp/Cntr=0.3,0.1

Type RM Length L Ch R = 1 ,5247.5  ,808.23,833.695,863.315
XS GIS Cut Line= 3
     1769672.475      323741.883     1770302.205      323112.365
     1770396.927      322626.172
#Sta/Elev= 30
       0 1125.26    35.2 1123.98    80.5 1119.81   130.9 1117.76   169.5  1117.8
   214.9    1122     287 1123.02   318.1 1120.95   332.4 1116.86     366 1102.01
   416.4 1082.95   454.8 1063.97   589.1 1017.66   639.5  997.44   668.3   983.7
   689.9  978.35   706.7  972.68   712.7  972.99   729.5  977.98   740.2   978.8
   796.6  978.18   911.9  980.28     924  978.81   933.6  976.14   948.6   973.9
   996.5   980.5  1141.7  980.79  1202.2  985.92  1298.9  991.84  1385.8 1000.13
#Mann= 3 , 0 , 0
       0      .1       0   933.6    .045       0   948.6      .1       0
Bank Sta=933.6,948.6
XS Rating Curve= 0 ,0
Exp/Cntr=0.3,0.1

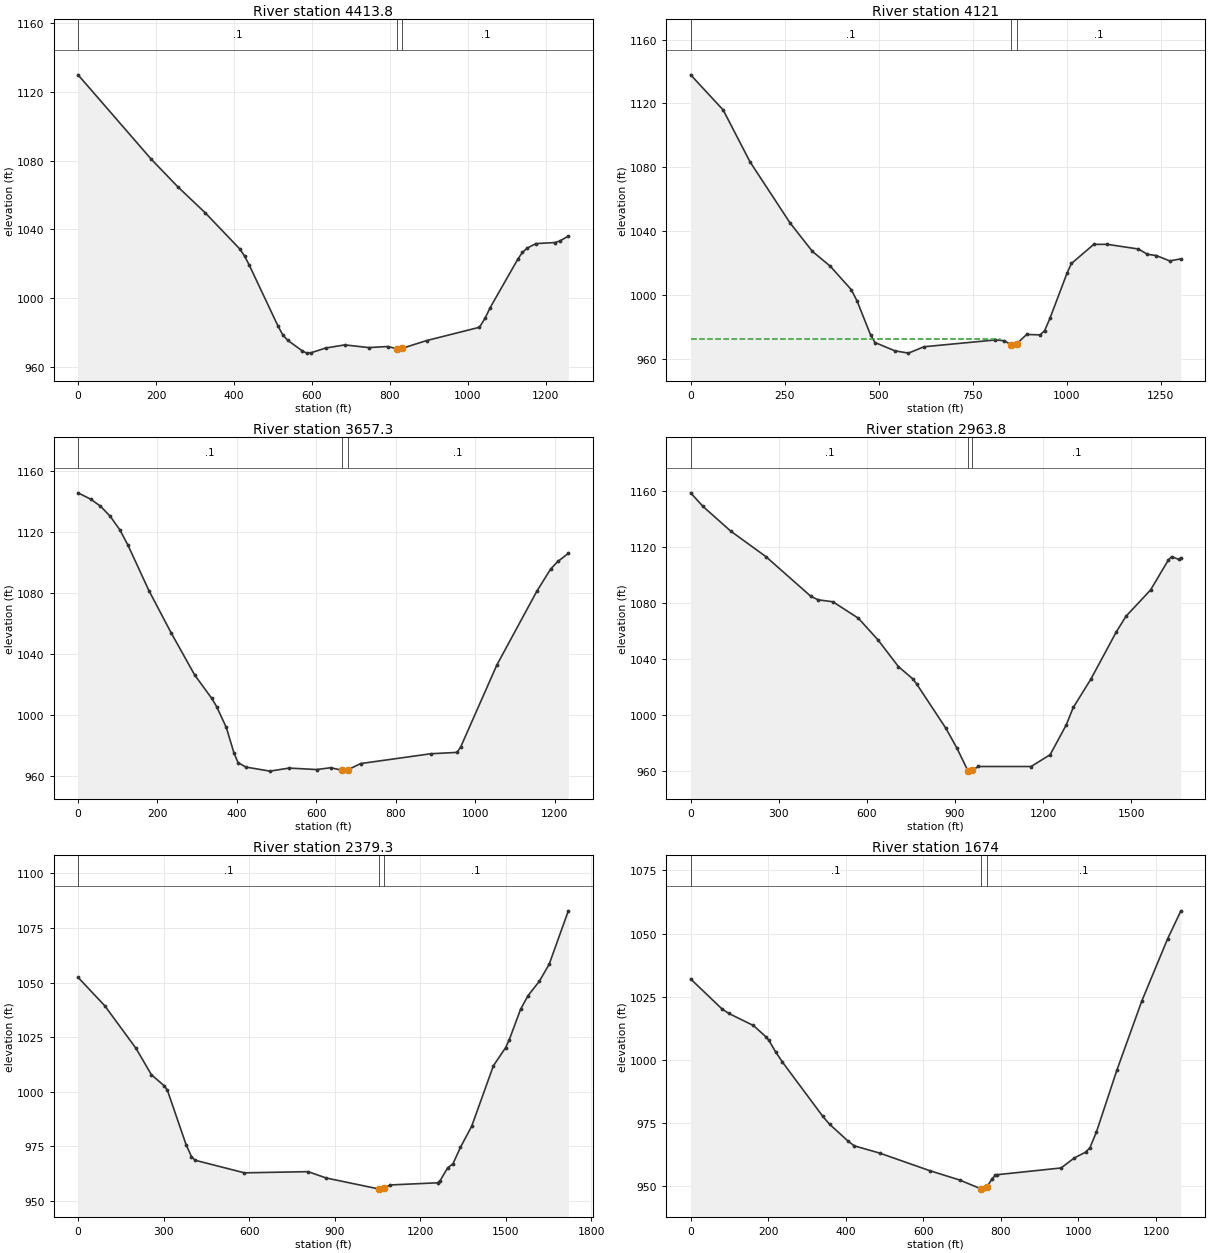
Type RM Length L Ch R = 1 ,4413.8  ,287.326,292.76,294.041
XS GIS Cut Line= 3
     1769733.626      323877.968     1770533.017      323680.362
     1770966.541      323658.284
#Sta/Elev= 30
       0 1130.06   188.3 1080.76   256.1 1064.78   325.6 1049.82   415.1 1028.54
   427.4 1024.42   439.6 1018.99     513  983.64   525.2   978.5   537.4  975.49
   574.1  969.39   586.3  967.93   598.6  968.23   635.3  970.91   684.2  972.73
   745.3  971.17   794.3  971.78   816.9  970.54   831.9  970.78   893.9  975.24
  1029.6     983  1044.7  988.57  1056.6  994.26  1127.9 1022.67  1139.8 1026.61
  1151.7 1029.06  1174.2 1031.74    1223 1032.35  1234.9  1033.2  1257.5 1036.08
#Mann= 3 , 0 , 0
       0      .1       0   816.9    .045       0   831.9      .1       0
Bank Sta=816.9,831.9
XS Rating Curve= 0 ,0
Exp/Cntr=0.3,0.1

Type RM Length L Ch R = 1 ,4121    ,446.578,463.738,480.897
XS GIS Cut Line= 3
     1769753.202      323972.475     1770645.412      323959.343
     1771056.615      323936.069
#Sta/Elev= 30
       0 1137.93    86.6  1115.9   157.9 1083.44   264.7 1045.05   324.1 1027.25
   371.6 1017.96   427.3 1003.31   442.8  996.19   478.5  975.04   490.3  970.19
   543.2  964.99   579.4  963.53   620.9  967.53   810.9  971.79   834.7   971.3
   852.2  968.76   867.2   969.4     894  975.23   929.7  974.97   941.6  977.57
   955.8  985.33  1001.1 1013.55    1013 1019.71  1072.4 1031.69  1108.1 1031.71
  1191.3 1028.78  1215.1 1025.46  1238.9 1024.67  1274.6 1021.32  1304.2 1022.62
#Mann= 3 , 0 , 0
       0      .1       0   852.2    .045       0   867.2      .1       0
#XS Ineff= 2 , 0
          822.97   972.1
Permanent Ineff=
       F       F
Bank Sta=852.2,867.2
XS Rating Curve= 0 ,0
Exp/Cntr=0.3,0.1

Type RM Length L Ch R = 1 ,3657.3  ,704.852,693.473,678.894
XS GIS Cut Line= 3
     1769725.334      324028.625     1770320.269      324166.069
     1770762.878      324605.733
#Sta/Elev= 30
       0 1145.38    32.2 1141.16    56.4 1136.66    80.9 1130.05   105.3 1121.12
   125.7 1111.09   178.4 1081.37   234.5 1053.65   293.9 1025.99   336.8 1010.73
     349 1005.33   373.1  991.85   392.9  974.79   402.8  968.77   422.1  965.82
   483.1  963.13   531.5  965.13   600.8  964.16   636.2  965.37   663.6  963.79
   678.6  963.89   711.4  968.08   888.2  974.51   954.2  975.41   963.3  978.86
  1054.6 1032.67    1155 1080.86  1189.9 1095.46  1208.3 1100.49  1234.5  1105.7
#Mann= 3 , 0 , 0
       0      .1       0   663.6    .045       0   678.6      .1       0
Bank Sta=663.6,678.6
XS Rating Curve= 0 ,0
Exp/Cntr=0.3,0.1

Type RM Length L Ch R = 1 ,2963.8  ,603.726,584.528,571.253
XS GIS Cut Line= 3
     1769067.815      324424.836     1769974.377      324701.355
      1770690.15      324793.344
#Sta/Elev= 30
       0 1158.51    41.8 1148.85   136.8 1131.12   256.2 1112.98   409.9 1084.51
   434.7 1082.07   484.4  1080.7   571.3 1068.94   638.1 1053.44   707.8 1034.34
   757.5 1025.47   769.9 1021.91   869.2  990.34   906.4  976.34   944.6  959.85
   955.8  959.74   959.6  960.42   979.7  963.05  1159.3  963.04  1224.2  971.45
    1279  992.73  1302.9 1005.19  1362.8  1025.4  1449.9 1059.34  1482.5 1070.35
  1566.2 1089.14  1627.2 1110.69  1638.1 1112.93    1662 1111.01  1669.5 1112.01
#Mann= 3 , 0 , 0
       0      .1       0   944.6    .045       0   959.6      .1       0
Bank Sta=944.6,959.6
XS Rating Curve= 0 ,0
Exp/Cntr=0.3,0.1

Type RM Length L Ch R = 1 ,2379.3  ,709.633,705.267,699.31
XS GIS Cut Line= 3
     1769295.331      325824.931     1770114.386      325163.386
     1770714.976      324874.374
#Sta/Elev= 30
       0  1052.4    93.8 1039.39   203.5 1019.85   257.3 1007.82   303.1 1002.65
   313.3 1000.72   379.4  975.61   397.7  970.38   409.9  968.69   583.4  962.91
   806.7  963.45   870.5  960.54  1056.7  955.48  1064.4  955.45  1071.7  955.78
  1094.6  957.36    1261  958.35  1269.9  959.38  1296.6  965.25  1314.7  967.03
    1341  974.58  1380.6  984.28  1456.7 1011.96  1499.2 1020.17  1512.3 1023.86
  1551.9 1037.77  1578.2 1044.05  1617.7 1050.61  1652.4 1058.46  1719.4 1082.86
#Mann= 3 , 0 , 0
       0      .1       0  1056.7    .045       0  1071.7      .1       0
Bank Sta=1056.7,1071.7
XS Rating Curve= 0 ,0
Exp/Cntr=0.3,0.1

Type RM Length L Ch R = 1 ,1674    ,436.263,428,418.352
XS GIS Cut Line= 3
     1770152.889      326094.449     1770670.924      325541.412
     1771040.155      325194.999
#Sta/Elev= 30
       0 1032.02    80.4 1020.21    97.8 1018.41   161.8 1013.59   194.3  1009.1
     202 1007.66   219.3  1003.1   236.7  999.11   340.7  977.63   358.3  974.49
   405.8  967.83   422.1  965.93   487.2  963.08   617.3  956.07   693.6  952.41
   748.8   948.9   757.7   948.8   763.8  949.62   777.6     953     786  954.29
   790.3  954.51     955  957.18   989.7  961.18  1018.2  963.43  1029.6   965.2
  1046.4  971.48  1099.6  996.16  1163.2 1023.26  1229.8  1047.9  1264.1 1058.99
#Mann= 3 , 0 , 0
       0      .1       0   748.8    .045       0   763.8      .1       0
Bank Sta=748.8,763.8
XS Rating Curve= 0 ,0
Exp/Cntr=0.3,0.1

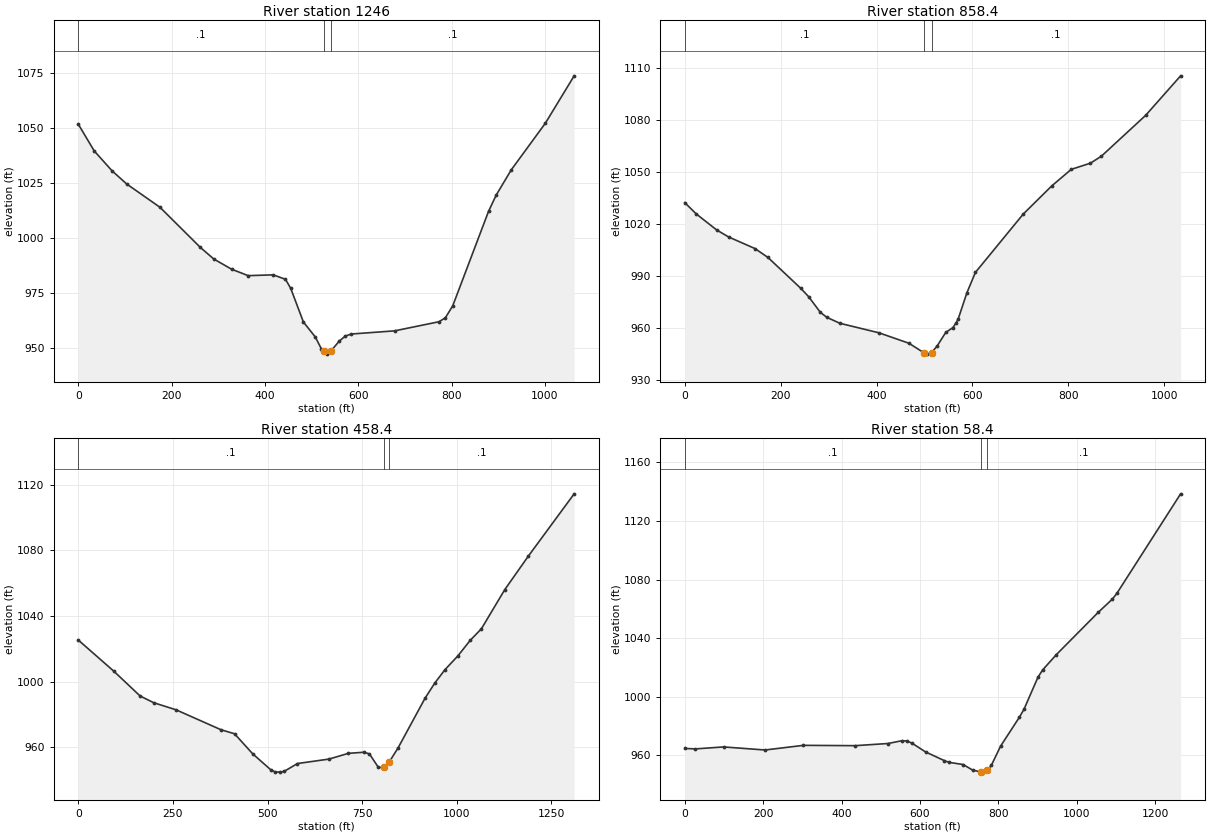
Type RM Length L Ch R = 1 ,1246    ,385.626,387.6,392.826
XS GIS Cut Line= 3
      1770809.99      326245.378     1771043.021       325670.77
     1771259.166      325284.328
#Sta/Elev= 30
       0 1051.53    34.1 1039.42    72.5 1030.33   103.8 1024.38     175 1013.81
   261.7  995.54   290.3   990.3   328.7  985.64   364.1  982.73   417.6   983.1
     444  981.08   455.2  976.98   482.5  961.63   508.1  954.81   520.9  949.48
   526.2  948.49   533.7  947.06   541.2  948.43   559.3  952.98   572.2  955.26
     585   956.2     678  957.64   773.2  961.79   786.8   963.6   802.5  968.99
   879.2 1011.92   895.7 1019.35   927.9  1030.8  1000.9 1051.97  1062.8 1073.56
#Mann= 3 , 0 , 0
       0      .1       0   526.2    .045       0   541.2      .1       0
Bank Sta=526.2,541.2
XS Rating Curve= 0 ,0
Exp/Cntr=0.3,0.1

Type RM Length L Ch R = 1 ,858.4   ,410.33,400,392.512
XS GIS Cut Line= 3
      1771075.77      326365.056     1771324.583      325922.929
     1771637.473      325499.161
#Sta/Elev= 30
       0 1032.42    23.7 1025.94    66.6 1016.64    91.8 1012.57   146.3 1005.96
   173.5  1000.8   241.7  983.08   258.4  978.18   282.5  969.25   296.2  966.31
   323.4  962.89   405.1  957.38   467.6  951.37   499.8  945.69   505.9  945.11
   514.8  946.03   526.2  949.76   544.2  957.59     559  960.37   566.1  963.19
   570.5  965.62   588.5  980.55   606.1   992.2     706 1025.86   765.6 1042.11
     806 1051.58     846 1055.14   868.9 1059.18     961 1082.67  1034.1 1105.48
#Mann= 3 , 0 , 0
       0      .1       0   499.8    .045       0   514.8      .1       0
Bank Sta=499.8,514.8
XS Rating Curve= 0 ,0
Exp/Cntr=0.3,0.1

Type RM Length L Ch R = 1 ,458.4   ,403.814,400,393.552
XS GIS Cut Line= 3
     1771615.988         326840.     1771644.185       326026.15
     1771788.069      325551.828
#Sta/Elev= 30
       0 1025.27    93.5 1006.38   163.2  991.22   198.9  987.14   258.3  982.79
   377.1  970.64   412.7  968.21   460.9  955.94   507.8   946.4   519.6  944.98
   531.5  944.84   543.4  945.25     579  950.08   662.2  952.78   713.5  956.28
   754.9  956.96   769.1  955.94   792.9  947.69   806.8  947.71   821.8  951.13
   844.9  959.66     916  989.84     942  999.17   968.7 1007.26  1002.8 1015.64
  1035.3  1025.1  1064.9 1032.15  1126.9 1056.08  1188.9  1076.4    1310 1114.36
#Mann= 3 , 0 , 0
       0      .1       0   806.8    .045       0   821.8      .1       0
Bank Sta=806.8,821.8
XS Rating Curve= 0 ,0
Exp/Cntr=0.3,0.1

Type RM Length L Ch R = 1 ,58.4    ,56.464,58.428,56.933
XS GIS Cut Line= 3
     1772137.523      326822.499     1772033.276      326065.171
     1772040.874      325564.645
#Sta/Elev= 30
       0  964.71    27.2  964.42    99.1  965.76   204.8  963.67   302.8  966.84
   434.7  966.62   518.5   968.1   554.5  970.03   566.2  969.77   578.5  968.53
   614.4  962.34   662.4  956.39   674.3  955.23   710.3  953.74   734.3  949.96
     757  948.59   758.2  948.56   770.2  949.17     772  949.77     782  953.11
   805.8  966.32   853.3  985.87   865.2  991.33   900.8 1013.16   912.7 1018.22
   948.1 1028.79  1055.1 1057.68  1090.8 1066.63  1102.6 1070.65  1265.1 1138.53
#Mann= 3 , 0 , 0
       0      .1       0     757    .045       0     772      .1       0
Bank Sta=757,772
XS Rating Curve= 0 ,0
Exp/Cntr=0.3,0.1

Chan Stop Cuts=-1
Use User Specified Reach Order=0